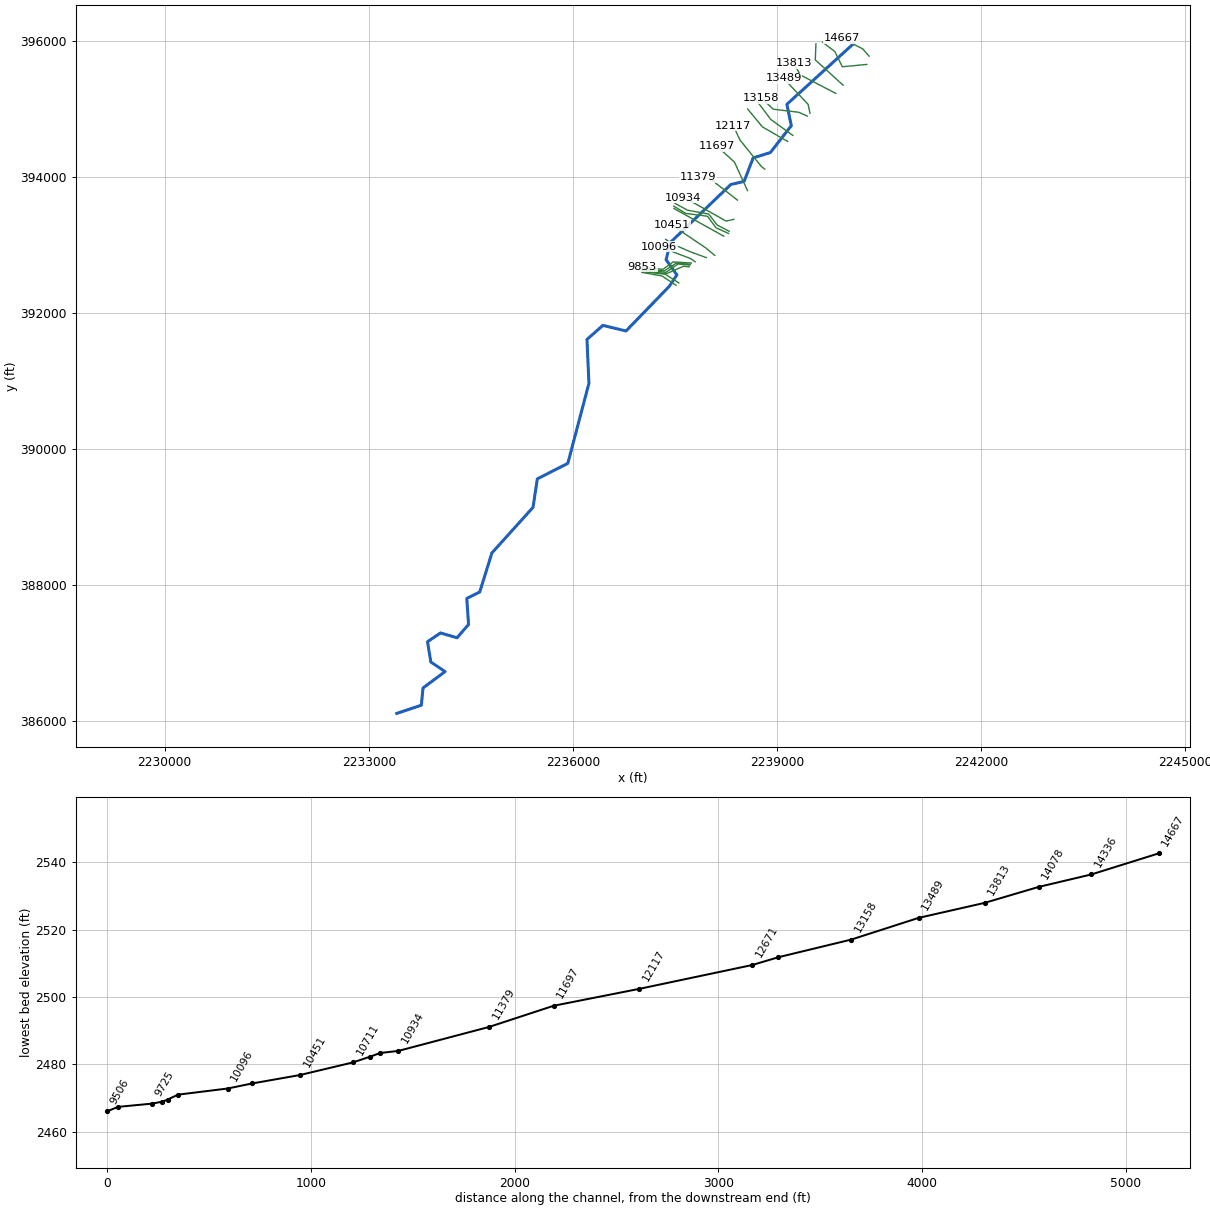
--- NFANTNYCK.prj (project) ---

Proj Title=NFANTNYCK
Current Plan=p01
Default Exp/Contr=0,0
English Units
Geom File=g01
Flow File=f01
Plan File=p01
Background Map Layer=Inundation Boundary (01pct Value_0)
BEGIN DESCRIPTION:
----------MODEL BY WOOD PLC 2021----------
Stream Name: North Fork Anthony Creek
Flood Zone: Approximate
Pocahontas County, WV
HEC-RAS Version: RAS 6.1
Vertical Datum: NAVD88
Projection: NAD 1983 StatePlane West Virginia S FIPS 4702 (US Feet)
Terrain: 1-meter LIDAR (FEMA Region III 3DEP collected 2016-2018)
Land Use: 2019 NLCD
Hydrologic Method:
WV SIR2010-5033 regression equations
END DESCRIPTION:
DSS File=dss
DSS Export Rating Curves= 0
DSS Export Rating Curve Sorted= 0
DSS Export Volume Flow Curves= 0
DXF OffsetX= 0
DXF OffsetY= 0
DXF ScaleX= 0
DXF ScaleY= 0

--- NFANTNYCK.p01 (plan) ---

Plan Title=Floodplain
Program Version=6.10
Short Identifier=NFANTNYCK
Geom File=g01
Flow File=f01
Subcritical Flow
K Sum by GR= 0
Std Step Tol= 0.01
Critical Tol= 0.01
Num of Std Step Trials= 20
Max Error Tol= 0.3
Flow Tol Ratio= 0.001
Split Flow NTrial= 30
Split Flow Tol= 0.02
Split Flow Ratio= 0.02
Log Output Level= 0
Friction Slope Method= 1
Unsteady Friction Slope Method= 2
Unsteady Bridges Friction Slope Method= 1
Parabolic Critical Depth
Global Vel Dist= 0 , 0 , 0
Global Log Level= 0
CheckData=True
Encroach Param=-1 ,0,0, 0
Computation Interval=0.1SEC
Output Interval=1SEC
Instantaneous Interval=Max Profile
Mapping Interval=1HOUR
Computation Time Step Use Courant=        0
Computation Time Step Use Time Series=    0
Computation Time Step Count To Double=0
Computation Time Step Max Doubling=0
Computation Time Step Max Halving=0
Computation Time Step Residence Courant=0
Run HTab= 0
Run UNet= 0
Run Sediment= 0
Run PostProcess= 0
Run WQNet= 0
Run RASMapper=-1
UNET Theta= 0
UNET Theta Warmup= 0
UNET ZTol= 0
UNET ZSATol= 0
UNET MxIter= 0
UNET Max Iter WO Improvement= 0
UNET MaxInSteps= 0
UNET DtIC= 0
UNET DtMin= 0
UNET MaxCRTS= 0
UNET WFStab= 0
UNET SFStab= 0
UNET WFX= 1
UNET SFX= 1
UNET Gravity=32.174
UNET 1D Methodology=Finite Difference
UNET DSS MLevel= 1
UNET Pardiso=0
UNET DZMax Abort= 0
UNET Use Existing IB Tables= 0
UNET Froude Reduction=False
UNET Froude Limit= 0
UNET Froude Power= 0
UNET D1 Cores= 0
UNET WindReference=Eulerian
UNET WindDragFormulation=Hsu (1988)
UNET D2 Coriolis=0
UNET D2 Cores= 0
UNET D2 Theta= 1
UNET D2 Theta Warmup= 1
UNET D2 Z Tol= 0.01
UNET D2 Volume Tol= 0.01
UNET D2 Max Iterations= 20
UNET D2 Equation= 0
UNET D2 RampUpFraction=0.1
UNET D2 TimeSlices= 1
UNET D2 Turbulence Formulation=Non-Conservative (original)
UNET D2 Smagorinsky Mixing=0
UNET D2 BCVolumeCheck=0
UNET D2 Cores=0
UNET D2 SolverType=PARDISO (Direct)
UNET D2 Minimum Iterations= 2147483647
UNET D2 Maximum Iterations= 2147483647
UNET D2 Restart Number= 10
UNET D2 Relaxation Coeff=1.3
UNET D2 SOR Precondition Iterations= 10
UNET D2 ILUT Maximum Fill= 8
UNET D2 ILUT Tolerance=1E-08
UNET D1D2 MaxIter= 0
UNET D1D2 ZTol=0.01
UNET D1D2 QTol=0.1
UNET D1D2 MinQTol=1
DSS File=dss
Write IC File= 0
Write IC File at Fixed DateTime=0
Write IC File at Sim End=0
Echo Input=False
Echo Parameters=False
Echo Output=False
Write Detailed= 0
HDF Write Warmup=0
HDF Write Time Slices=0
HDF Flush=0
HDF Compression= 1
HDF Chunk Size= 1
HDF Spatial Parts= 1
HDF Use Max Rows=0
HDF Fixed Rows= 1
Calibration Method= 0
Calibration Iterations= 20
Calibration Max Change=0.05
Calibration Tolerance=0.2
Calibration Maximum=1.5
Calibration Minimum=0.5
Calibration Optimization Method= 1
WQ AD Non Conservative
WQ ULTIMATE=-1
WQ Max Comp Step=1HOUR
WQ Output Interval=15MIN
WQ Output Selected Increments= 0
WQ Output face flow=0
WQ Output face velocity=0
WQ Output face area=0
WQ Output face dispersion=0
WQ Output cell volume=0
WQ Output cell surface area=0
WQ Output cell continuity=0
WQ Output cumulative cell continuity=0
WQ Output face conc=0
WQ Output face dconc_dx=0
WQ Output face courant=0
WQ Output face peclet=0
WQ Output face adv mass=0
WQ Output face disp mass=0
WQ Output cell mass=0
WQ Output cell source sink temp=0
WQ Output nsm pathways=0
WQ Output nsm derived pathways=0
WQ Create Restart=0
WQ Fixed Restart=0
WQ System Summary=0
WQ Write To DSS=0
Sorting and Armoring Iterations= 10
XS Update Threshold= 0.02
Bed Roughness Predictor= 0
Hydraulics Update Threshold= 0.02
Energy Slope Method= 1
Volume Change Method= 1
Sediment Retention Method= 0
Sediment TS Multiplier= 1
Warm Up Method= 0
XS Weighting Method= 0
Number of US Weighted Cross Sections= 1
Number of DS Weighted Cross Sections= 1
Upstream XS Weight=0
Main XS Weight=1
Downstream XS Weight=0
Number of DS XS's Weighted with US Boundary= 1
Upstream Boundary Weight= 1
Weight of XSs Associated with US Boundary= 0
Number of US XS's Weighted with DS Boundary= 1
Downstream Boundary Weight= 0.5
Weight of XSs Associated with DS Boundary= 0.5
Percentile Method= 0
Sediment Output Level= 3
Mass or Volume Output= 0
Output Increment Type= 1
Profile and TS Output Increment= 1
Transport Output Increment 1
XS Output Flag= 0
XS Output Increment= 10
Read HDF5 Sediment Hotstart= 0
Sediment Hotstart Type= 0
Write Gradation File= 0
Read Gradation Hotstart= 0
Write HDF5 File= 1
Write Binary Output= 1
Write DSS Sediment File= 0
DSS Sediment Output Type= 1
SV Curve= 0
Specific Gage Flag= 0
Subcell Erosion Methods= 0
Subcell Deposition Methods= 0
Advection Scheme= 1
Matrix Solver= 0
Implicit Weighting Factor= 1
Maximum Outer Loop Convergence Iterations= 5
Convergence Maximum Absolute= 0.001
Convergence RMSE= 0.0001
Grain Fractions Max Abs Error= 0.001
Max Subgrid Regions= 1
Max Subgrid Length Scale= 3.402823E+38
Initial Layer Thickness= 3.402823E+38
Min Layer Thickness= 3.402823E+38
Max Layer Thickness= 3.402823E+38
Number of Layers= 5

--- NFANTNYCK.f01 (steady flow) ---

Flow Title=Flow
Program Version=6.10
Number of Profiles= 6
Profile Names=01pct,10pct,04pct,02pct,0_2pct,01plus
River Rch & RM=NFANTNYCK,Main,14667
     707     377     499     600     984    1050
River Rch & RM=NFANTNYCK,Main,9853
     888     477     630     755    1230    1310
River Rch & RM=NFANTNYCK,Main,7842
    1030     555     731     874    1420    1520
River Rch & RM=NFANTNYCK,Main,6821
    1160     629     825     986    1600    1710
River Rch & RM=NFANTNYCK,Main,3921
    1390     757     991    1180    1900    2050
Boundary for River Rch & Prof#=NFANTNYCK,Main            , 1
Up Type= 0
Dn Type= 1
Dn Known WS=2382.1
Boundary for River Rch & Prof#=NFANTNYCK,Main            , 2
Up Type= 0
Dn Type= 1
Dn Known WS=2381.4
Boundary for River Rch & Prof#=NFANTNYCK,Main            , 3
Up Type= 0
Dn Type= 1
Dn Known WS=2381.7
Boundary for River Rch & Prof#=NFANTNYCK,Main            , 4
Up Type= 0
Dn Type= 1
Dn Known WS=2381.9
Boundary for River Rch & Prof#=NFANTNYCK,Main            , 5
Up Type= 0
Dn Type= 1
Dn Known WS=2382.6
Boundary for River Rch & Prof#=NFANTNYCK,Main            , 6
Up Type= 0
Dn Type= 1
Dn Known WS=2382.7
DSS Import GetInterval= 0
DSS Import GetPeak= 0
DSS Import FillOption= 0

--- NFANTNYCK.g01 (geometry) ---

Geom Title=Geometry
Program Version=6.10

River Reach=NFANTNYCK       ,Main
Reach XY= 30
2240121.13200003395958.0900000182239143.27500005395068.354000002
2239207.81600001394754.1879999942238900.15200002394359.005999997
2238647.15633804394280.7629577672238515.01184399393936.062025741
2238317.66900001393888.7539999932237431.31700003393038.421000004
2237367.88200001392786.108999997     2237526.892392560.628000021
2237412.75600003392391.3789999932236779.35200003391737.353000015
2236439.14500003391819.383000001     2236205.355391612.611000016
2236234.07900003 390967.718000012235923.77499999389791.604000002
       2235475.7389563.7450000052235412.44200002389144.756000012
2234808.18400005388475.2000000182234629.35017459387900.637894109
2234439.02882501387807.8211187422234465.06700002387424.016000018
      2234295.83387228.8780000212234052.52700001387299.616999999
2233862.29400001387170.6400000162233911.14499998      386871.191
     2234120.495386732.195000008     2233796.244386491.595000014
2233770.99400002386236.893000007 2233411.3070107386117.645227477

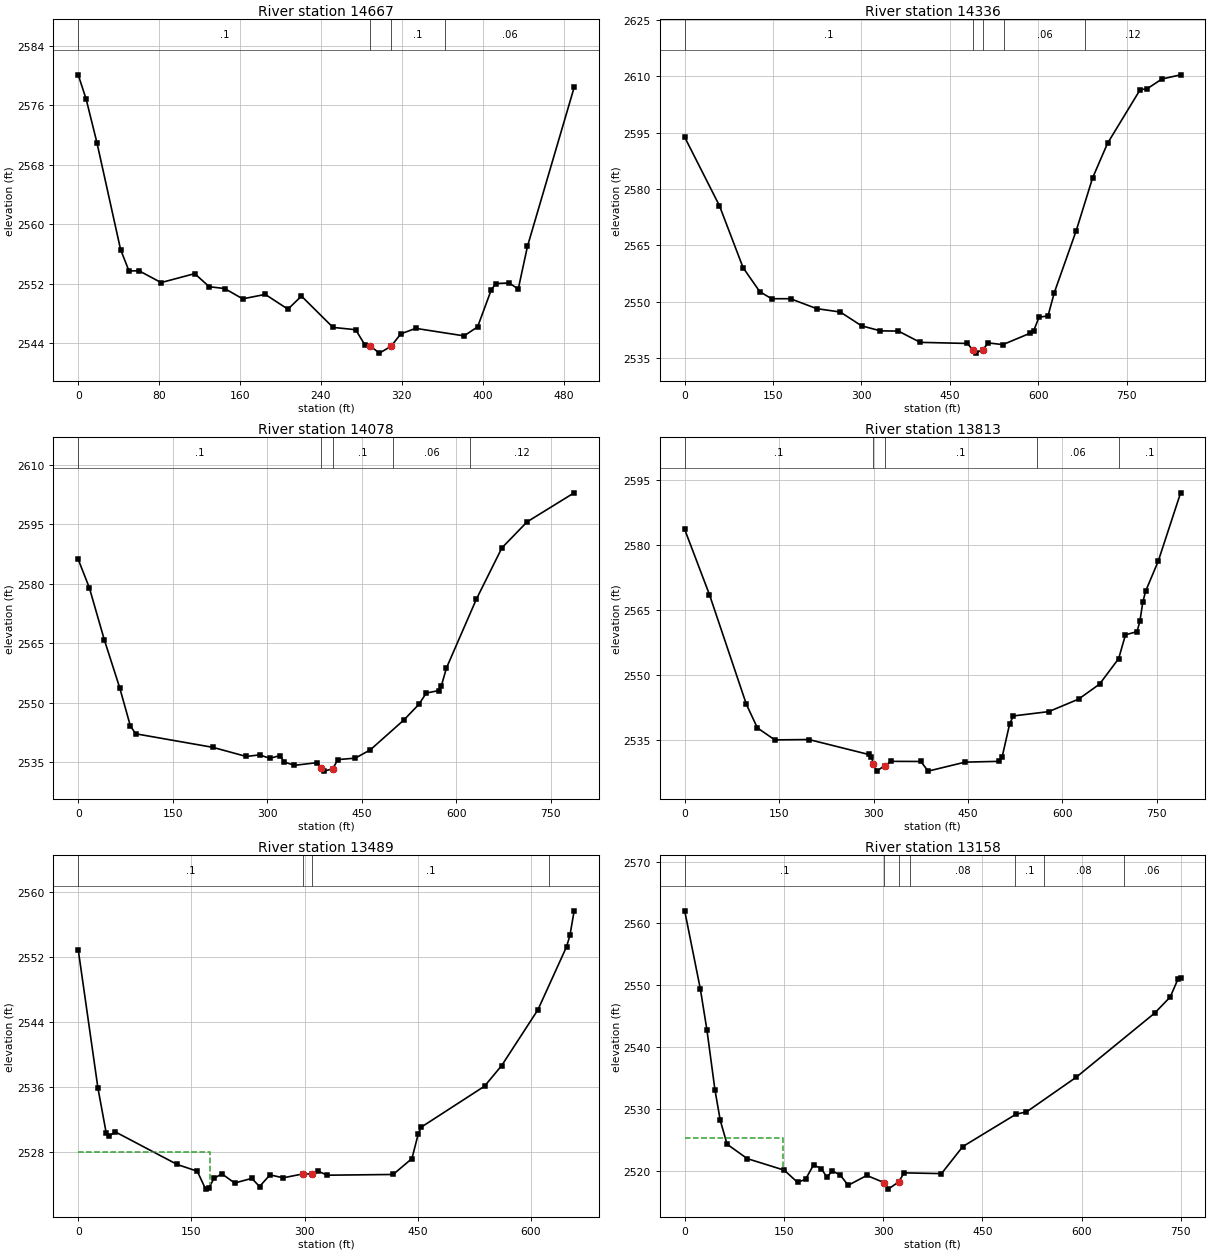
Type RM Length L Ch R = 1 ,14667   ,331.1,331.1,331.1
XS GIS Cut Line= 3
2240351.58924735395775.2086701882240258.32777331395882.851585608
2239946.60987917396037.721156571
#Sta/Elev= 30
       0 2580.08     7.9 2576.78    18.5 2570.96    41.9 2556.58    50.2 2553.71
    60.2 2553.72      82 2552.14   115.2 2553.34   129.6 2551.58   144.8 2551.34
   162.7 2549.95     185 2550.55   207.4 2548.56   220.8 2550.32     252 2546.11
   274.4  2545.8   283.3 2543.81     289 2543.58   297.9 2542.65   309.5 2543.58
     319 2545.24   333.8 2545.98   381.6 2544.97     395 2546.18   408.3 2551.08
   412.8 2552.01   426.3 2552.09   435.2 2551.26   444.3    2557   490.5 2578.39
#Mann= 4 ,-1,0
       0      .1       0     289    .045       0   309.5      .1       0
  362.42     .06       0
Bank Sta=289,309.5
XS Rating Curve= 0 ,0
Exp/Cntr=0.3,0.1

Type RM Length L Ch R = 1 ,14336   ,252.7,258.3,263.3
XS GIS Cut Line= 4
2240318.95329505395654.2770773082239957.97549316  395619.8161893
2239849.42369593395842.0889169552239665.91946729 395983.37855779
#Sta/Elev= 30
       0 2593.77      59 2575.55    99.2 2559.07   127.4 2552.73   147.4 2550.85
   179.6 2550.84     224 2548.21   264.1 2547.31   300.1 2543.65   332.3  2542.3
   362.6 2542.25   399.7 2539.25   479.9 2538.96   488.8 2537.24   493.6 2536.39
   505.6 2537.32   515.5  2539.1   539.9 2538.65   586.7 2541.71   592.3 2542.36
   601.3 2545.91   616.6  2546.3   627.3 2552.49   664.4 2568.92   692.3 2582.97
   717.6 2592.14   773.1 2606.43   784.2 2606.57   809.9 2609.22   841.6 2610.33
#Mann= 5 ,-1,0
       0      .1       0   488.8    .045       0   505.6      .1       0
  542.62     .06       0  679.98     .12       0
Bank Sta=488.8,505.6
XS Rating Curve= 0 ,0
Exp/Cntr(USF)=0,0
Exp/Cntr=0.3,0.1

Type RM Length L Ch R = 1 ,14078   ,261.2,265.4,268.4
XS GIS Cut Line= 3
2239969.17528176395349.2982184332239560.81375886395720.614286725
2239569.42898086395955.809847383
#Sta/Elev= 30
       0 2586.17    17.7 2578.98    41.4 2565.87    65.8 2553.78    82.7 2544.14
    91.2 2542.12   213.9 2538.69   266.8 2536.39   287.9  2536.8   304.1 2535.92
   320.3 2536.62   326.8 2535.02   343.2 2534.15   379.8 2534.84   386.22533.418
   390.6 2532.69     4042533.288   412.2  2535.6   439.8 2535.97   463.6 2538.05
   517.1 2545.62   540.9 2549.57   552.5  2552.4   572.5 2553.04   576.5 2554.22
   584.5 2558.71   632.1 2576.12   672.6 2589.07   712.6 2595.64   787.3 2602.97
#Mann= 5 ,-1,0
       0      .1       0   386.2    .045       0     404      .1       0
     500     .06       0  621.94     .12       0
Bank Sta=386.2,404
XS Rating Curve= 0 ,0
Exp/Cntr(USF)=0,0
Exp/Cntr=0.3,0.1

Type RM Length L Ch R = 1 ,13813   ,321.4,323.7,318.2
XS GIS Cut Line= 3
2239863.11619618 395227.817933952239340.53755893  395500.1876962
2239244.52030918395673.854211091
#Sta/Elev= 30
       0 2583.58    39.4 2568.55      98 2543.32   115.5  2537.9   143.1 2535.14
   197.3 2535.22     292 2531.79   296.7 2531.27   299.7 2529.49   305.5    2528
   317.5  2529.2   328.1  2530.2   375.1 2530.17   386.7 2527.95   445.4 2530.02
   499.5  2530.2   504.3 2531.25   516.2 2538.85     522 2540.65   578.4 2541.65
   625.6 2544.52     659 2547.98   689.3 2553.85   700.1 2559.33   718.4 2560.04
     723 2562.42   727.6  2566.8   732.1 2569.36   752.2 2576.29   787.7    2592
#Mann= 5 ,-1,0
       0      .1       0   299.7    .045       0   317.5      .1       0
     560     .06       0   689.3      .1       0
Bank Sta=299.7,317.5
XS Rating Curve= 0 ,0
Exp/Cntr=0.3,0.1

Type RM Length L Ch R = 1 ,13489   ,316.2,331.2,340
XS GIS Cut Line= 3
2239483.09727643394937.0436023882239454.99640624395067.402521045
2239095.58756542395448.568112701
#Sta/Elev= 30
       0 2552.92    26.1 2535.93      37 2530.44    41.1 2530.04    49.2 2530.53
   131.1 2526.53   157.8  2525.7   168.8  2523.5   173.4 2523.67   179.8 2524.81
   190.4 2525.38   207.3 2524.25     230 2524.82   240.3 2523.82   254.1 2525.25
   271.6 2524.89   297.9 2525.37  310.18 2525.36   318.2  2525.7   329.9 2525.21
   417.3  2525.3   442.2 2527.25   450.7 2530.31   454.7 2531.12   538.4 2536.14
   561.1 2538.67   609.2 2545.53   647.1 2553.26   651.6 2554.66   657.2 2557.68
#Mann= 4 ,-1,0
       0      .1       0   297.9    .045       0  310.18      .1       0
  623.35     .06       0
#XS Ineff= 2 , 0
             175    2528
Permanent Ineff=
       F       F
Bank Sta=297.9,310.18
XS Rating Curve= 0 ,0
Exp/Cntr(USF)=0,0
Exp/Cntr=0.3,0.1

Type RM Length L Ch R = 1 ,13158   ,360.7,356.9,334.3
XS GIS Cut Line= 4
2239442.99451596394895.7633091812239314.65104507394951.393602299
2238943.61101303394996.2635596622238769.60147123395155.750710043
#Sta/Elev= 30
       0 2562.04    23.7 2549.39    33.6 2542.81    45.8 2533.06    53.8 2528.16
    64.1 2524.31    94.6 2521.98   150.4 2520.12   170.6 2518.15   182.7 2518.64
   194.8 2520.96   206.8 2520.36   214.9 2518.96     223 2519.98     235 2519.36
   247.1 2517.67   275.3 2519.26   301.9 2518.08   307.6 2517.05   323.4  2518.2
   331.7 2519.68   388.2 2519.56   420.4 2523.93     501 2529.17   516.7 2529.53
   591.9 2535.14   710.3 2545.49     734 2548.11     746 2551.08   749.7 2551.17
#Mann= 7 ,-1,0
       0      .1       0   301.9    .045       0   323.4      .1       0
  339.88     .08       0  499.88      .1       0  543.62     .08       0
  663.62     .06       0
#XS Ineff= 2 , 0
          148.21  2525.3
Permanent Ineff=
       F       F
Bank Sta=301.9,323.4
XS Rating Curve= 0 ,0
Exp/Cntr=0.3,0.1

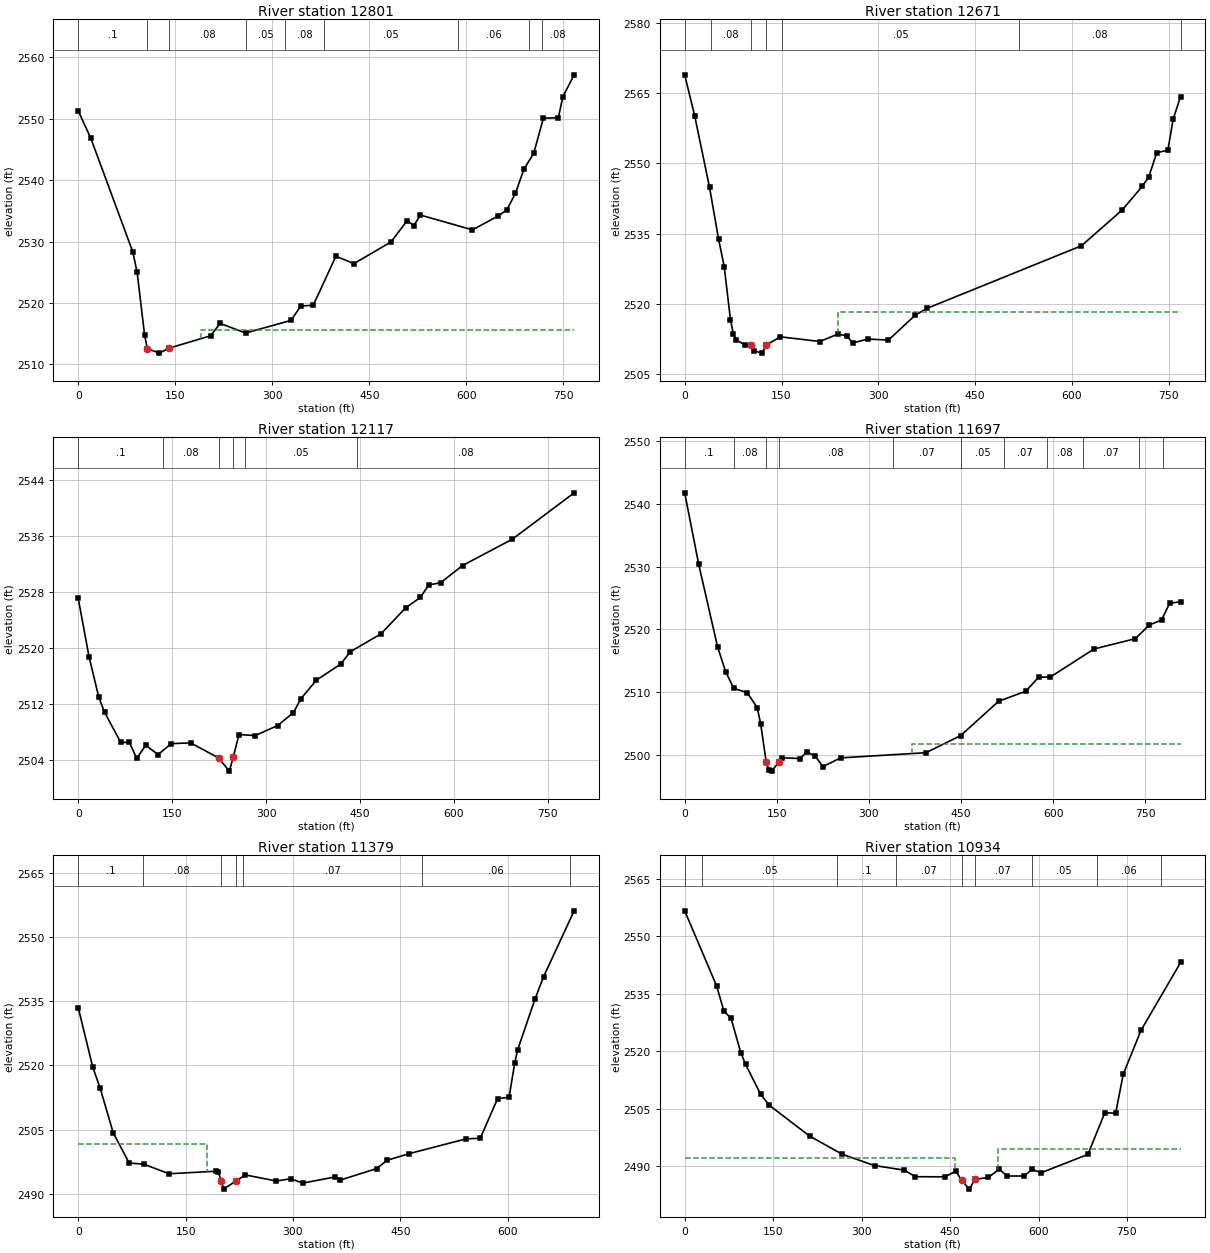
Type RM Length L Ch R = 1 ,12801   ,128.1,129.4,130.8
XS GIS Cut Line= 3
2239229.98923398 394611.83521505 2238907.7799311394844.446209108
2238685.50720345395139.086801581
#Sta/Elev= 30
       0 2551.29    19.5 2546.82    84.3 2528.33    91.1 2524.97   102.5 2514.85
   106.72512.566   125.5 2511.82   140.4 2512.63   204.5 2514.64   219.3 2516.66
   258.8  2515.1   328.9 2517.15     344 2519.49   363.3 2519.63   398.3  2527.6
   426.2 2526.41   483.3 2529.92   508.5  2533.4   518.6 2532.59     529 2534.31
   609.3  2531.9   649.1 2534.17   662.4 2535.15   675.7 2537.85   688.9  2541.8
     704 2544.37     719 2550.11   742.1 2550.15   748.9 2553.56   766.5 2557.16
#Mann= 9 ,-1,0
       0      .1       0   106.7    .045       0   140.4     .08       0
     260     .05       0     320     .08       0     380     .05       0
   587.4     .06       0   697.4     .07       0   717.4     .08       0
#XS Ineff= 2 , 0
                          189.51         2515.66
Permanent Ineff=
       F       F
Bank Sta=106.7,140.4
XS Rating Curve= 0 ,0
Exp/Cntr(USF)=0,0
Exp/Cntr=0.3,0.1

Type RM Length L Ch R = 1 ,12671   ,556.5,554.8,543.7
XS GIS Cut Line= 3
2239153.54750955394522.9735266792238782.52048823394737.122921134
2238566.52546267394999.396476575
#Sta/Elev= 30
       0 2568.93    15.4 2560.24    38.5 2544.89    52.4 2533.92    61.2 2527.99
    70.9 2516.66    75.5 2513.51    80.1 2512.32      94 2511.16   103.2 2511.26
     108 2509.96   119.8 2509.49   126.3 2511.24   148.4 2512.97   209.4 2511.97
   237.1 2513.55     251 2513.18   260.5 2511.65   283.3  2512.5   315.6 2512.27
   357.2 2517.61   375.7 2519.07   614.6 2532.42   677.5 2540.04   708.6 2545.08
   718.7 2547.07   731.3  2552.3   748.4 2552.83   756.9  2559.6   768.2 2564.29
#Mann= 7 ,-1,0
       0      .1       0      40     .08       0   103.2    .045       0
   126.3     .08       0     150     .05       0  518.39     .08       0
  768.16     .06       0
#XS Ineff= 2 , 0
                          237.97         2518.34
Permanent Ineff=
       F       F
Bank Sta=103.2,126.3
XS Rating Curve= 0 ,0
Exp/Cntr=0.3,0.1

Type RM Length L Ch R = 1 ,12117   ,421,419.5,411.9
XS GIS Cut Line= 4
2238817.73542935394115.4071122692238766.72910297394156.629901765
2238453.05555995394544.011365296  2238357.855565394751.084816636
#Sta/Elev= 30
       0 2527.06    17.4 2518.69    32.9 2512.94    42.2 2510.79    67.8 2506.52
    81.7 2506.51    93.4 2504.23   107.8  2506.1   127.5 2504.77   148.6 2506.33
   179.5 2506.44   224.2 2504.29   241.3 2502.41   247.6 2504.42   256.7 2507.63
   282.5 2507.48   318.5 2508.92   343.7 2510.77   355.7 2512.75   380.2 2515.38
   419.2 2517.69   434.7 2519.46   483.2 2521.98   522.8  2525.7   546.4  2527.2
   559.8 2528.99   578.5 2529.28   613.7 2531.75     693 2535.49   791.9 2542.12
#Mann= 6 ,-1,0
       0      .1       0  135.58     .08       0   224.2    .045       0
   247.6     .08       0  265.58     .05       0  445.58     .08       0
Bank Sta=224.2,247.6
XS Rating Curve= 0 ,0
Exp/Cntr=0.3,0.1

Type RM Length L Ch R = 1 ,11697   ,310.8,318.1,324.8
XS GIS Cut Line= 3
2238564.13592429393800.4813955642238373.13393176394218.166494714
2238116.34861087394453.289365694
#Sta/Elev= 30
       0 2541.79    22.8  2530.4    53.5 2517.24    66.7 2513.26    79.9 2510.61
   101.9 2509.91   118.2 2507.52   123.9 2504.85   132.7 2498.86   137.1 2497.58
   141.5  2497.4  153.492498.848   159.1 2499.53   187.6 2499.41   198.7 2500.42
   211.8 2499.89   225.1 2498.12     254 2499.51   392.9 2500.34   449.4 2503.07
   511.1 2508.54   555.5 2510.15   576.3 2512.39   595.2  2512.4   666.7 2516.89
   733.9 2518.53   756.5 2520.71   776.4  2521.5   789.5 2524.15   807.5 2524.44
#Mann= 11 ,-1,0
       0      .1       0      80     .08       0   132.7    .045       0
  153.49     .08       0     340     .07       0     450     .05       0
  519.28     .07       0  589.28     .08       0  649.28     .07       0
  739.28     .06       0  779.28     .08       0
#XS Ineff= 2 , 0
                          369.87         2501.75
Permanent Ineff=
       F       F
Bank Sta=132.7,153.49
XS Rating Curve= 0 ,0
Exp/Cntr=0.3,0.1

Type RM Length L Ch R = 1 ,11379   ,439.8,444.7,445.5
XS GIS Cut Line= 3
2238416.27898509393660.6669680852238008.45346996393978.827980037
     2237833.579      393994.647
#Sta/Elev= 30
       0 2533.52    20.4 2519.54    30.6 2514.71    48.9 2504.24    71.2 2497.19
    91.6 2496.92     127 2494.68   192.9 2495.28   195.9 2495.02   199.9 2492.92
   203.1 2491.09   219.9 2492.94   233.5 2494.41   276.9 2492.98   296.8 2493.52
   313.9  2492.5   358.5 2493.93   365.4 2493.17     417  2495.9   431.4 2497.83
   462.5 2499.39   541.6 2502.83   561.7 2502.99   585.8 2512.22   601.9 2512.57
   609.9 2520.67   613.9 2523.66     638 2535.46   650.1 2540.74   692.8 2556.12
#Mann= 7 ,-1,0
       0      .1       0      90     .08       0   199.9    .045       0
   219.9     .08       0     230     .07       0     480     .06       0
  687.25     .07       0
#XS Ineff= 2 , 0
           180.2 2501.69
Permanent Ineff=
       F       F
Bank Sta=199.9,219.9
XS Rating Curve= 0 ,0
Exp/Cntr=0.3,0.1

Type RM Length L Ch R = 1 ,10934   ,81,89,91.6
XS GIS Cut Line= 4
2238364.93979755393378.0969770492238249.44763367393352.054626373
2237718.41013509393652.1077972132237614.24073239393695.134289635
#Sta/Elev= 30
       0 2556.57    54.1 2537.01    66.4 2530.47    78.7 2528.49    95.1 2519.62
   103.3 2516.51     129 2508.67   143.6 2505.85   211.7 2497.84     267 2493.09
     322 2490.13   372.6 2488.94   390.9 2487.23   441.5  2487.2   459.8 2488.69
   469.5 2486.33   482.8 2483.99     492 2486.52     515 2487.04   533.3 2489.17
   547.1 2487.41     576 2487.41   588.5 2489.11   604.7 2488.27   683.8 2493.05
   712.5 2503.93   730.8 2503.77   743.7 2513.96   773.7 2525.37     841  2543.1
#Mann= 9 ,-1,0
       0     .08       0      30     .05       0  258.39      .1       0
  358.39     .07       0   469.5    .045       0     492     .07       0
  588.39     .05       0  698.39     .06       0  808.34      .1       0
#XS Ineff= 2 , 0
          458.59 2492.23  532.13         2494.55
Permanent Ineff=
       T       T
Bank Sta=469.5,492
XS Rating Curve= 0 ,0
Exp/Cntr(USF)=0,0
Exp/Cntr=0.5,0.3

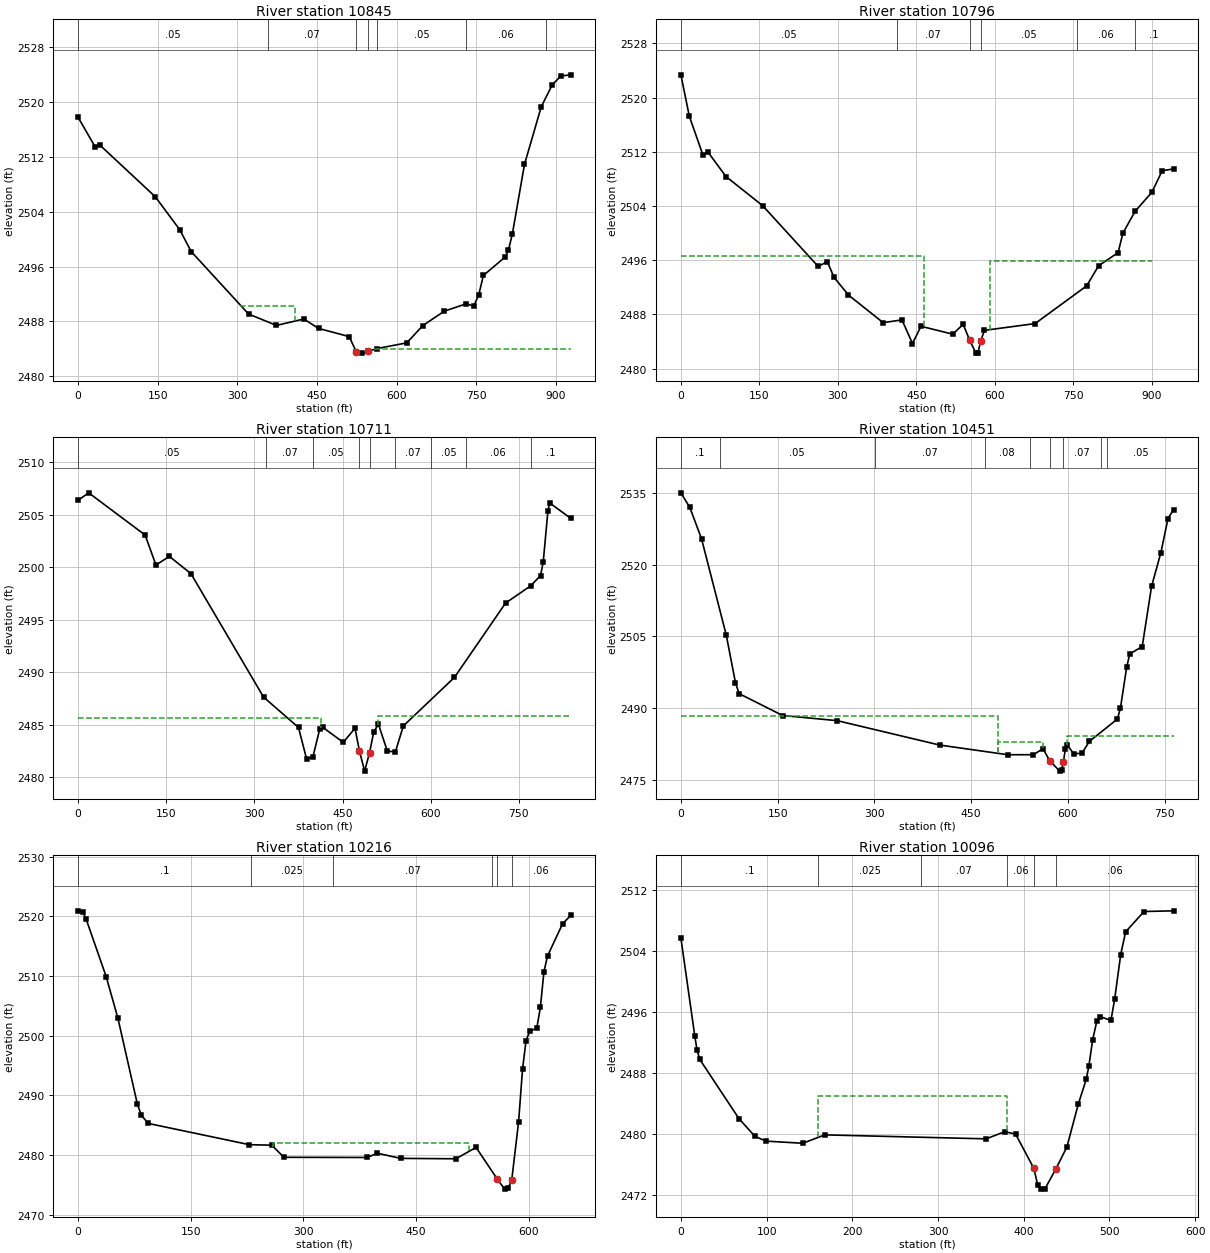
Type RM Length L Ch R = 1 ,10845   ,51.2,49.2,50.6
XS GIS Cut Line= 5
2238295.25589088393202.4404131182238119.12405055393293.302076778
2237994.57367775393455.2594975732237681.59019323393512.767941311
2237499.86686591393612.016835463
#Sta/Elev= 30
       0  2517.8    32.1 2513.48    40.9 2513.75   145.6 2506.18   191.4 2501.39
   213.2 2498.18   321.1 2489.07   373.6 2487.41   425.3 2488.34   452.9 2486.97
   510.7 2485.77   523.8 2483.58   535.1 2483.36   545.9 2483.62   562.5 2484.02
   619.2 2484.86     649 2487.36   689.6 2489.48   731.4 2490.57   745.1 2490.22
   754.5 2491.82   763.4  2494.7     805 2497.43   810.5 2498.38     818 2500.77
   840.8 2510.91   872.4 2519.33     893 2522.52   909.2 2523.82   927.8 2523.99
#Mann= 7 ,-1,0
       0     .05       0  358.19     .07       0   523.8    .045       0
   545.9     .07       0   562.5     .05       0  730.72     .06       0
  880.72      .1       0
#XS Ineff= 3 ,-1
  305.26  408.42 2490.18  408.42  515.61    2484  557.71   927.8    2484
Permanent Ineff=
       F       F       F
Bank Sta=523.8,545.9
XS Rating Curve= 0 ,0
Exp/Cntr(USF)=0,0
Exp/Cntr=0.5,0.3

Type RM Length L Ch R = 1 ,10796   ,91.6,85.2,79.7
XS GIS Cut Line= 5
2238286.86866039  393170.28936292238102.34958957393252.763796069
2237976.54113219  393423.30414942237656.42850176393465.240301858
2237481.69453318393571.478554753
#Sta/Elev= 30
       0 2523.36    16.1 2517.26    42.4 2511.47    51.1 2512.03    86.2 2508.35
   156.3 2504.05   262.3 2495.09   279.9 2495.79   292.6 2493.48   320.3 2490.86
   386.5 2486.79   422.5 2487.19   442.6 2483.71   458.8 2486.25   519.5 2485.09
   539.5 2486.54   551.6 2484.25   563.7 2482.29   567.7 2482.37     573 2484.08
   580.1 2485.65   676.9 2486.65   775.3 2492.21   798.4 2495.19   835.5 2497.12
   844.7 2499.99     868 2503.22   900.1 2506.03   919.8 2509.21   941.4 2509.47
#Mann= 6 ,-1,0
       0     .05       0  412.11     .07       0   551.6    .045       0
     573     .05       0  756.88     .06       0  866.88      .1       0
#XS Ineff= 4 ,-1
       0  465.22 2496.66  465.22     550    2484     575     591    2484
     591     900 2495.82
Permanent Ineff=
       F       F       F       F
Bank Sta=551.6,573
XS Rating Curve= 0 ,0
Exp/Cntr(USF)=0,0
Exp/Cntr=0.5,0.3

Type RM Length L Ch R = 1 ,10711   ,260.2,259.9,259
XS GIS Cut Line= 2
2238216.03164154393129.9629475652237483.35788038393537.090395737
#Sta/Elev= 30
       0 2506.38    18.1 2507.09   114.2 2503.06   132.5 2500.21   155.4 2501.03
     192 2499.39   315.6 2487.62   375.1 2484.72   388.8 2481.73   399.4 2481.87
   411.1 2484.54   416.3 2484.74   451.3  2483.3   471.2 2484.65   478.8 2482.48
   487.6 2480.56     496 2482.32   503.2 2484.31   511.1 2485.03   526.1 2482.49
   539.8 2482.37   553.5 2484.87   640.5  2489.5   727.4 2496.58     770 2498.22
   786.9  2499.2   791.5 2500.51   799.4 2505.31   802.4 2506.13   838.2 2504.66
#Mann= 9 ,-1,0
       0     .05       0     320     .07       0     400     .05       0
   478.8    .045       0     496     .05       0     540     .07       0
     600     .05       0     660     .06       0     770      .1       0
#XS Ineff= 2 , 0
          414.08 2485.67  509.86          2485.8
Permanent Ineff=
       F       T
Bank Sta=478.8,496
XS Rating Curve= 0 ,0
Exp/Cntr=0.3,0.1

Type RM Length L Ch R = 1 ,10451   ,234.4,235.5,234.6
XS GIS Cut Line= 3
2238082.89031743 392848.865263112237950.86909673392957.588621336
2237460.06079388393289.971459341
#Sta/Elev= 30
       0 2535.01    13.9 2531.95      32 2525.41    70.4 2505.25    84.6 2495.34
    90.2 2493.03   157.8 2488.45   242.5 2487.37   401.3 2482.27   506.8 2480.25
   546.3 2480.25   561.5  2481.5   571.8 2479.01   587.4 2476.82   590.3 2476.97
   593.2 2478.82   596.1 2481.44     599 2482.33   609.1 2480.42     622 2480.58
   633.2 2483.02   676.8 2487.71   681.5 2489.97   691.2 2498.55     696 2501.33
   715.3 2502.87   729.8 2515.46   744.3 2522.53   755.2 2529.61   763.8 2531.48
#Mann= 9 ,-1,0
       0      .1       0      60     .05       0  301.03     .07       0
  471.03     .08       0  541.03     .07       0   571.8    .045       0
   593.2     .07       0  651.03     .06       0  661.03     .05       0
#XS Ineff= 3 ,-1
       0     492 2488.34     492  561.01 2482.84  598.52   763.8 2484.07
Permanent Ineff=
       F       T       F
Bank Sta=571.8,593.2
XS Rating Curve= 0 ,0
Exp/Cntr(USF)=0,0
Exp/Cntr=0.3,0.1

Type RM Length L Ch R = 1 ,10216   ,114.3,119.2,119.2
XS GIS Cut Line= 4
2237958.35392516 392815.368744972237715.04824368392904.580828179
 2237475.7976569393010.0132901532237362.25500554393083.004994596
#Sta/Elev= 30
       0 2520.91     6.6 2520.65    10.8 2519.51    37.4  2509.9      53 2502.96
      79 2488.51    84.2 2486.69    93.5 2485.31   228.1 2481.75   257.9 2481.67
   273.9 2479.64   384.7 2479.61   398.3 2480.32   429.3 2479.46   502.7 2479.39
   529.7 2481.29   558.2 2475.94   567.7 2474.31   572.5 2474.49   577.2 2475.86
   586.3  2485.6   591.5 2494.36   596.2 2499.16     601 2500.74   610.5 2501.25
   615.3 2504.77     620  2510.7   624.8 2513.36   644.8 2518.73   655.6 2520.15
#Mann= 6 ,-1,0
       0      .1       0     230    .025       0  339.15     .07       0
   550.6     .06       0   558.2    .045       0   577.2     .06       0
#XS Ineff= 1 ,-1
     260     520    2482
Permanent Ineff=
       T
Bank Sta=558.2,577.2
XS Rating Curve= 0 ,0
Exp/Cntr(USF)=0,0
Exp/Cntr=0.3,0.1

Type RM Length L Ch R = 1 ,10096   ,225.2,243.2,252.6
XS GIS Cut Line= 3
2237795.50873857392753.8047721482237730.03531717392800.195794287
2237268.00915889392976.544484413
#Sta/Elev= 30
       0 2505.74    16.3 2492.84    18.8 2491.08      22 2489.83    67.8 2482.05
    86.5 2479.73    99.4 2479.11   142.2 2478.83   167.9 2479.93   356.2 2479.41
   377.7 2480.34   390.5 2480.04   411.9 2475.53   416.2 2473.42   420.5 2472.82
   424.8 2472.86   437.6 2475.48   450.4 2478.34   463.6 2483.92   472.9 2487.19
     476 2488.91   480.4 2492.34   485.3 2494.83     489 2495.43   501.8 2494.93
   506.1 2497.68   513.2 2503.56   518.9 2506.53   540.4  2509.2   574.8 2509.29
#Mann= 6 ,-1,0
       0      .1       0  160.24    .025       0  280.24     .07       0
  380.24     .06       0   411.9    .045       0   437.6     .06       0
#XS Ineff= 1 ,-1
     160     380    2485
Permanent Ineff=
       T
Bank Sta=411.9,437.6
XS Rating Curve= 0 ,0
Exp/Cntr=0.3,0.1

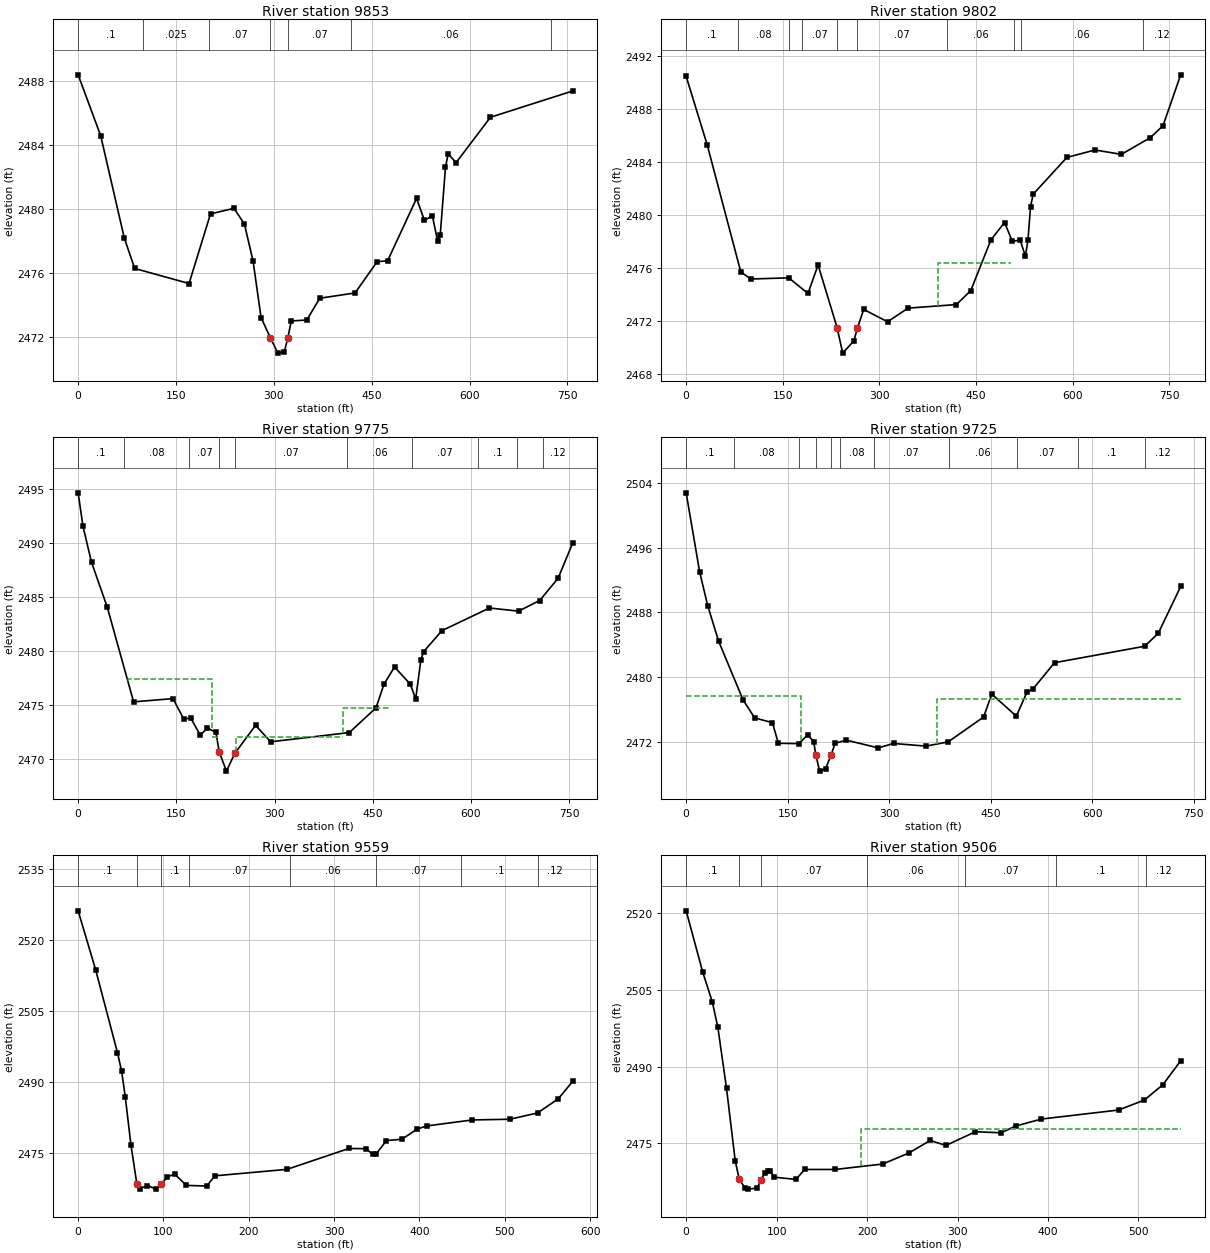
Type RM Length L Ch R = 1 ,9853    ,48.8,51.7,46.5
XS GIS Cut Line= 4
2237738.76908408392736.7579752632237470.96313704392751.432273732
2237319.63443408392642.2921788742237018.81131548392680.812212353
#Sta/Elev= 30
       0 2488.39    34.6 2484.58    70.7  2478.2    86.7 2476.29     170 2475.35
   202.9  2479.7     239 2480.05     255 2479.05   268.2 2476.74   280.4 2473.22
   294.7 2471.96   306.2    2471     316 2471.08  321.322471.935   326.8 2473.01
   350.6 2473.07   370.3 2474.43   424.5 2474.76   458.3 2476.71   474.4 2476.77
   518.8 2480.67   530.9 2479.29     543 2479.59     551 2478.01   555.1  2478.4
   563.1  2482.6   567.2 2483.46   579.3  2482.9   632.1 2485.74   758.1 2487.38
#Mann= 7 ,-1,0
       0      .1       0     100    .025       0     200     .07       0
   294.7    .045       0  321.32     .07       0  418.21     .06       0
  724.79     .12       0
Bank Sta=294.7,321.32
XS Rating Curve= 0 ,0
Exp/Cntr(USF)=0,0
Exp/Cntr=0.5,0.3

Type RM Length L Ch R = 1 ,9802    ,25.4,26.3,27.9
XS GIS Cut Line= 4
2237724.31632676392718.3482525962237520.09900641392733.939694719
2237338.30075316392619.5005476362236992.84331006392662.300584835
#Sta/Elev= 30
       0 2490.45    32.6 2485.29    84.8 2475.68   100.4 2475.14   159.3 2475.23
   189.1 2474.05   204.8  2476.2   234.3 2471.47     243 2469.54   260.4 2470.47
   265.9 2471.44   275.6 2472.84   312.6 2471.91   344.5 2472.94   419.6 2473.21
   441.9 2474.27   473.2 2478.11   494.3 2479.41   506.4 2477.98   518.5 2478.09
   526.6 2476.86   530.6 2478.09   534.6  2480.6   538.7 2481.55   591.1 2484.33
   634.6 2484.89   675.7 2484.56   720.7 2485.83   740.2 2486.72   767.7 2490.57
#Mann= 10 ,-1,0
       0      .1       0      80     .08       0     160    .025       0
     180     .07       0   234.3    .045       0   265.9     .07       0
  404.81     .06       0  509.63     .07       0  519.63     .06       0
  709.63     .12       0
#XS Ineff= 3 ,-1
       0  230.19  2472.1   271.7  390.74  2472.1  390.74  503.582476.328
Permanent Ineff=
       F       F       F
Bank Sta=234.3,265.9
XS Rating Curve= 0 ,0
Exp/Cntr(USF)=0,0
Exp/Cntr=0.5,0.3

Type RM Length L Ch R = 1 ,9775    ,55,50,48.9
XS GIS Cut Line= 4
2237716.46965327392705.4063365862237545.74427918392721.589336365
2237364.28649003392599.017672691 2237002.0147466392642.123424441
#Sta/Elev= 30
       0 2494.62     7.4 2491.52    20.4 2488.21    44.5 2484.05    84.7 2475.31
   144.9 2475.61     161 2473.75   172.2 2473.79   186.5 2472.23   197.5 2472.89
   210.4 2472.49   215.52470.676   226.5 2468.91   239.2 2470.54   270.9 2473.14
   294.1 2471.62   414.1 2472.47     455 2474.76   467.1 2476.94   483.2 2478.53
   507.4 2476.94   515.5 2475.57   523.5  2479.2   527.5 2479.94   555.7 2481.89
   628.2 2483.98   672.6 2483.69   704.8 2484.67     733 2486.72   755.3 2489.98
#Mann= 10 ,-1,0
       0      .1       0      70     .08       0     170     .07       0
   215.5    .045       0   239.2     .07       0  410.47     .06       0
  510.47     .07       0  610.47      .1       0  670.47     .06       0
  710.47     .12       0
#XS Ineff= 4 ,-1
   75.79  203.79 2477.39  203.79  212.72  2472.1  241.02     404  2472.1
  404.21  474.95 2474.72
Permanent Ineff=
       F       F       F       F
Bank Sta=215.5,239.2
XS Rating Curve= 0 ,0
Exp/Cntr(USF)=0,0
Exp/Cntr=0.5,0.3

Type RM Length L Ch R = 1 ,9725    ,183.5,166.7,141.2
XS GIS Cut Line= 4
2237708.02778238392681.0732329322237621.37469634392687.232217933
2237372.56186608392578.8924421232237003.29590656392625.583707112
#Sta/Elev= 30
       0 2502.83    19.9 2493.03    31.9 2488.82      48 2484.43    84.1 2477.15
   101.3 2474.92   127.4 2474.34   136.2 2471.78   166.7 2471.74   179.8 2472.86
   188.5 2471.93   191.42470.376   197.2 2468.33     206 2468.64     214 2470.32
     220 2471.78   236.5 2472.17   283.9 2471.21   306.3 2471.76   354.3 2471.43
   386.9 2471.95   439.4 2475.04   451.4 2477.88   487.7 2475.15   503.8 2478.19
   511.8 2478.46   544.1 2481.77   677.2 2483.81   697.3  2485.4   730.5 2491.22
#Mann= 11 ,-1,0
       0      .1       0      70     .08       0  166.87     .07       0
   191.4    .045       0     214     .07       0  226.87     .08       0
  276.87     .07       0  388.25     .06       0  488.25     .07       0
  578.25      .1       0  678.25     .12       0
#XS Ineff= 2 , 0
          170.11 2477.65  370.53         2477.25
Permanent Ineff=
       F       F
Bank Sta=191.4,214
XS Rating Curve= 0 ,0
Exp/Cntr=0.3,0.1

Type RM Length L Ch R = 1 ,9559    ,51,52.9,50.4
XS GIS Cut Line= 3
2237554.96384761392443.694887321 2237354.1995207392572.706463874
2237015.24694796392608.442757723
#Sta/Elev= 30
       0  2526.1    20.5 2513.67    46.1 2496.15    50.9 2492.32    55.2 2486.87
    61.9 2476.66   68.88 2468.38    72.6 2467.49    81.2 2468.11    91.5 2467.37
    97.5 2468.39   104.4 2469.94   113.1 2470.54   126.9 2468.15   150.7 2468.03
   160.2 2470.18   244.7 2471.54   317.3 2475.95   337.2  2475.9   345.3 2474.72
   349.3 2474.83   361.3 2477.62   379.2 2477.89   397.5 2480.05   408.3  2480.7
   461.9 2481.97   506.1 2482.12   538.3 2483.45   562.5 2486.41   579.5  2490.1
#Mann= 8 ,-1,0
       0      .1       0   68.88    .045       0    97.5      .1       0
     130     .07       0  248.64     .06       0  348.64     .07       0
  448.64      .1       0  538.64     .12       0
Bank Sta=68.88,97.5
XS Rating Curve= 0 ,0
Exp/Cntr(USF)=0,0
Exp/Cntr=0.3,0.1

Type RM Length L Ch R = 1 ,9506    ,116.7,117.2,117.9
XS GIS Cut Line= 3
2237513.31955682392409.1609700722237306.04509095392546.732518213
2237012.55912159392598.092562852
#Sta/Elev= 30
       0 2520.43    18.2 2508.54      29 2502.57      35 2497.72    44.6 2485.78
    54.2 2471.65    58.6 2468.02    65.1 2466.28    68.6 2466.07    78.2 2466.27
      83 2467.91    86.8 2469.19    90.3 2469.62    93.2 2469.53    97.4  2468.4
   121.4 2467.97     131 2469.91   164.6 2469.91   217.3 2470.97     246 2473.11
   269.8 2475.57   287.2  2474.6   319.7 2477.28   348.1 2477.07   364.4  2478.4
   392.8 2479.76   478.1 2481.52   506.5 2483.47   526.8 2486.43   546.7 2491.13
#Mann= 7 ,-1,0
       0      .1       0    58.6    .045       0      83     .07       0
     200     .06       0  308.77     .07       0  408.77      .1       0
  508.77     .12       0
#XS Ineff= 2 , 0
                          193.67         2477.89
Permanent Ineff=
       F       F
Bank Sta=58.6,83
XS Rating Curve= 0 ,0
Exp/Cntr(USF)=0,0
Exp/Cntr=0.3,0.1