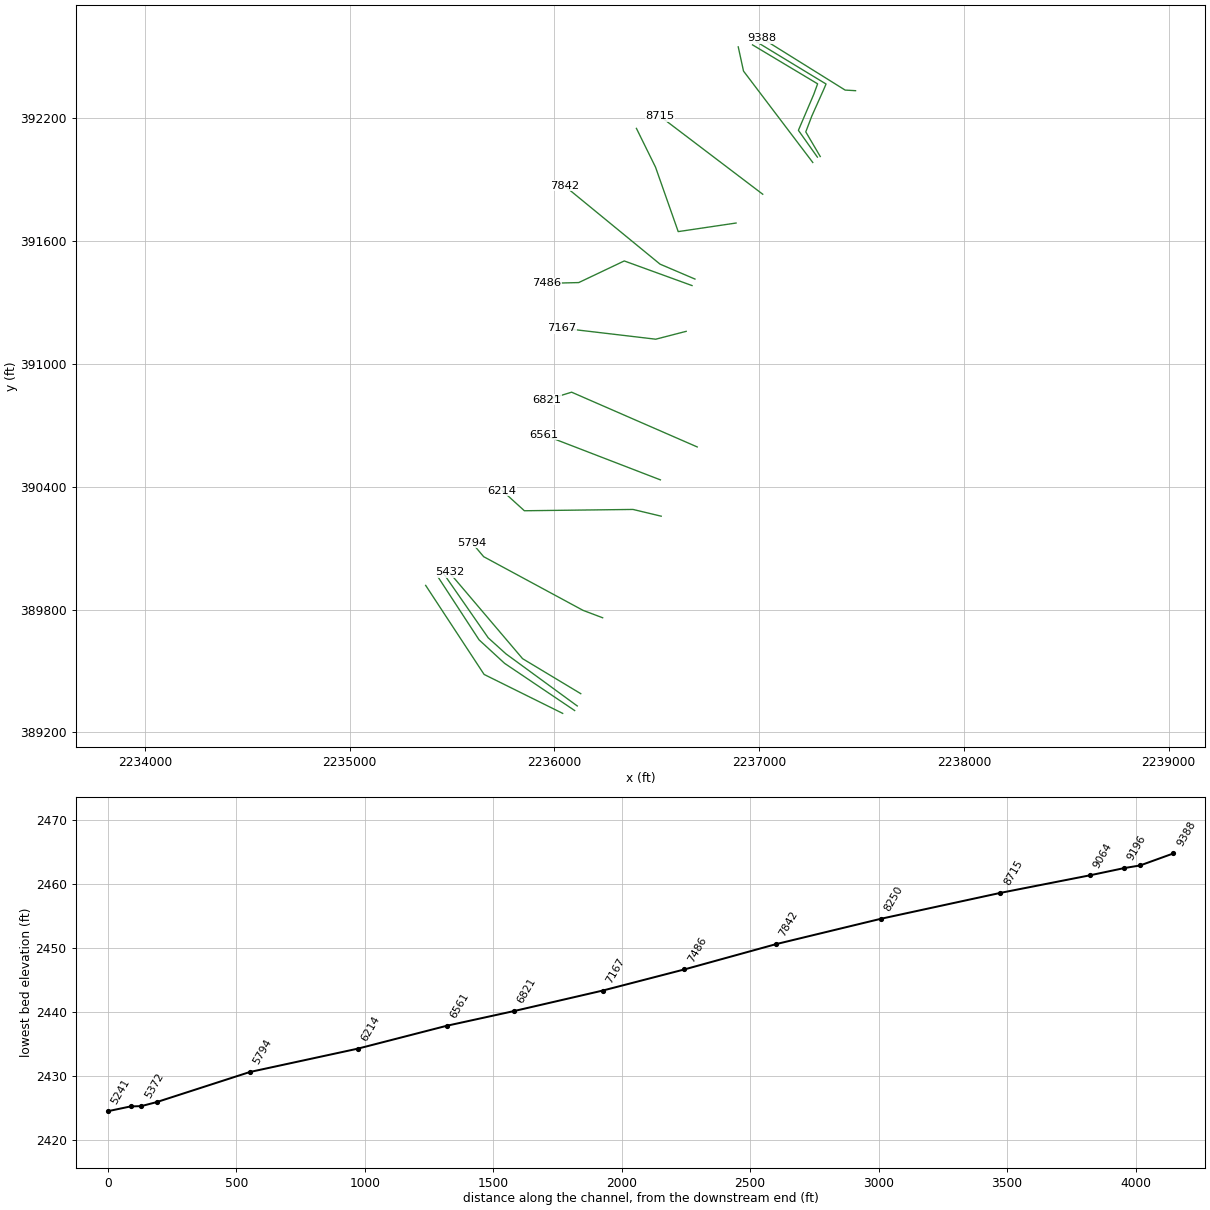
HEC-RAS study NFANTNYCK.prj: NFANTNYCK

--- NFANTNYCK.g01 (geometry) --- (continued)

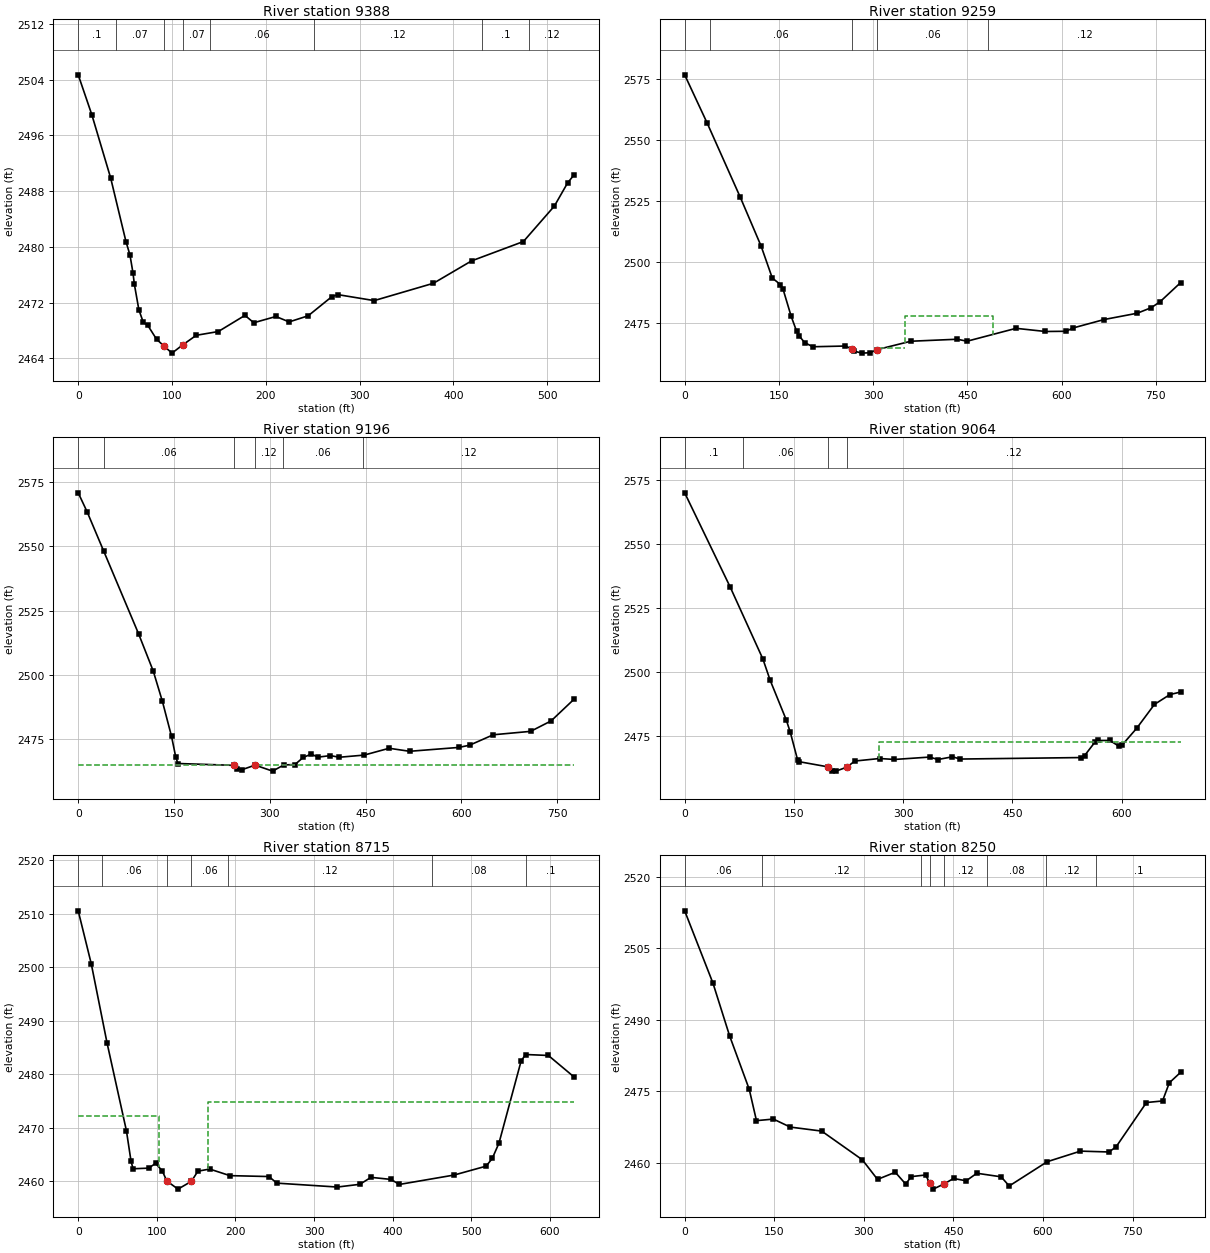
Type RM Length L Ch R = 1 ,9388    ,166,129.6,100.1
XS GIS Cut Line= 3
2237470.67515393392334.2688711592237419.82463354392337.224111823
2237014.24332866392589.948140998
#Sta/Elev= 30
       0 2504.69    14.5 2498.97    34.6 2489.88    50.9 2480.76    55.2 2478.82
    58.4 2476.25    59.9  2474.6    64.7 2470.95    69.4 2469.16    74.1 2468.74
    83.5 2466.74    91.3 2465.77     100 2464.74   111.4 2465.92   125.9  2467.3
   149.4 2467.84   177.8 2470.16   187.2  2469.1   210.8    2470   224.9 2469.22
   245.2  2470.1   270.2 2472.82   276.7 2473.14   315.6 2472.28   378.8 2474.77
   419.4 2477.98   474.7 2480.76   507.7 2485.85   521.8 2489.17   528.8 2490.35
#Mann= 8 ,-1,0
       0      .1       0      40     .07       0    91.3    .045       0
   111.4     .07       0  140.94     .06       0  250.94     .12       0
  430.94      .1       0  480.94     .12       0
Bank Sta=91.3,111.4
XS Rating Curve= 0 ,0
Exp/Cntr(USF)=0,0
Exp/Cntr=0.5,0.3

Type RM Length L Ch R = 1 ,9259    ,63.3,62.8,71.2
XS GIS Cut Line= 6
2237298.26559837392012.8511898982237227.64553699392132.997008607
2237256.99413393392210.0370755652237315.48038476392340.634663358
2237326.69705165392366.8686404452236988.27104323392572.308819001
#Sta/Elev= 30
       0 2576.85    35.7 2557.14    88.5  2526.7   121.6 2506.73   139.4 2493.63
   152.3 2490.96   156.7 2488.94   169.5 2477.93   178.1 2471.86   182.4 2469.84
   190.9 2467.19   203.8 2465.47   255.9 2465.77   265.9 2464.58   269.1  2463.7
   282.2 2462.86   295.4 2463.03   305.3 2464.23   359.8 2467.73   433.8 2468.55
   449.4 2467.74   527.4 2473.02   574.2 2471.72     607 2471.81   618.2 2473.17
   667.7 2476.63   720.2  2479.2   742.7 2481.49   756.7 2483.93   789.3 2491.74
#Mann= 5 ,-1,0
       0      .1       0      40     .06       0   265.9    .045       0
   305.3     .06       0  483.43     .12       0
#XS Ineff= 3 ,-1
     100     255  2464.8     311     350  2464.8     350     490    2478
Permanent Ineff=
       F       F       F
Bank Sta=265.9,305.3
XS Rating Curve= 0 ,0
Exp/Cntr(USF)=0,0
Exp/Cntr=0.5,0.3

Type RM Length L Ch R = 1 ,9196    ,101,132.2,148
XS GIS Cut Line= 5
 2237284.4113849 392009.681553722237191.64913807392140.715656893
2237267.08271412392317.3428831152237285.42558721392367.785784099
2236967.49422735392558.061315208
#Sta/Elev= 30
       0  2570.9    14.1 2563.42      40 2548.15    94.5 2515.99   117.5 2501.46
   131.8 2489.69   146.2 2475.95   152.7 2468.01   156.2 2465.41   243.9 2464.69
     248 2463.45   256.7 2463.02   277.1 2464.78   304.5 2462.44     322 2464.86
   339.4 2464.99   352.4 2467.78   365.2 2469.09   375.2 2467.88     395 2468.49
     409 2467.85   447.9 2468.69     487 2471.35     519 2470.17   595.9 2471.67
   612.9 2472.53   650.1 2476.61   708.6 2477.94   740.7 2482.01   776.8 2490.51
#Mann= 6 ,-1,0
       0      .1       0      40     .06       0   243.9    .045       0
   277.1     .12       0  320.55     .06       0  446.28     .12       0
#XS Ineff= 2 , 0
          241.44  2464.8  280.87          2464.8
Permanent Ineff=
       F       F
Bank Sta=243.9,277.1
XS Rating Curve= 0 ,0
Exp/Cntr=0.5,0.3

Type RM Length L Ch R = 1 ,9064    ,340.4,348.8,350.3
XS GIS Cut Line= 3
2237261.87211531391983.6142806772236923.54801173392429.957525754
2236897.80184996392548.246568636
#Sta/Elev= 30
       0 2569.83    62.3 2533.22   107.4 2505.05   117.4 2496.74   139.4 2481.37
   145.1 2476.42   155.1 2465.67   157.6 2464.98   196.5    2463   202.7 2461.45
   207.8 2461.32   222.8 2462.88   233.6 2465.25   267.7 2466.24   288.1 2465.87
   336.4  2466.8   347.8 2465.85   367.8 2466.91   378.4 2466.03     544 2466.61
   549.1 2467.34   563.4 2472.61   567.5 2473.27   583.8 2473.28   596.1 2471.08
   600.2 2471.32   620.7    2478   645.2 2487.35   666.5 2491.19   681.1 2492.16
#Mann= 4 ,-1,0
       0      .1       0      80     .06       0   196.5    .045       0
   222.8     .12       0
#XS Ineff= 2 , 0
                          267.19          2472.5
Permanent Ineff=
       F       F
Bank Sta=196.5,222.8
XS Rating Curve= 0 ,0
Exp/Cntr(USF)=0,0
Exp/Cntr=0.3,0.1

Type RM Length L Ch R = 1 ,8715    ,476.1,465.3,449.2
XS GIS Cut Line= 2
2237017.38174736391828.5539466912236514.98998656392209.951968634
#Sta/Elev= 30
       0 2510.54    16.6 2500.65    36.7 2485.85    61.3 2469.49    67.2 2463.77
    69.8 2462.37    89.8 2462.49    98.4  2463.4     107 2461.96   112.6  2460.1
   126.9 2458.57     144 2460.03   152.2 2461.92   167.2 2462.32   192.9 2461.09
   242.6 2460.92   252.6 2459.69   329.6 2458.96   358.2 2459.47   372.4 2460.77
     398 2460.38   408.3 2459.44   478.1  2461.2   518.8 2462.86   526.6 2464.29
   535.2 2467.17   563.3 2482.48     569 2483.71     598 2483.53   630.8  2479.5
#Mann= 7 ,-1,0
       0      .1       0      30     .06       0   112.6    .045       0
     144     .06       0     190     .12       0     450     .08       0
     570      .1       0
#XS Ineff= 2 , 0
          102.33  2472.2  165.12         2474.76
Permanent Ineff=
       F       F
Bank Sta=112.6,144
XS Rating Curve= 0 ,0
Exp/Cntr=0.3,0.1

Type RM Length L Ch R = 1 ,8250    ,395.7,407.7,406.6
XS GIS Cut Line= 4
2236887.06612033391687.8587247962236604.56119017391645.956079653
2236493.72193527391960.9017673442236400.45475737392150.139519604
#Sta/Elev= 30
       0 2512.88    47.4  2497.7    75.3 2486.64   108.1 2475.45   120.2 2468.88
   148.5 2469.21   176.8 2467.53   229.4 2466.69   297.5 2460.67   322.9 2456.56
   352.6 2458.06     370 2455.59   379.4 2457.14   403.5 2457.49  409.952455.838
   416.2 2454.52   434.42455.623   450.2 2456.75   471.4 2456.27   489.2 2457.85
   529.9  2457.1   543.4 2455.18     607 2460.27   662.7 2462.49   710.5 2462.31
   722.4  2463.4   773.2 2472.68   800.1 2473.01   811.5 2476.82   830.4 2479.01
#Mann= 8 ,-1,0
       0     .06       0     130     .12       0   395.6     .07       0
  409.95    .045       0   434.4     .12       0   505.6     .08       0
   605.6     .12       0  689.48      .1       0
Bank Sta=409.95,434.4
XS Rating Curve= 0 ,0
Exp/Cntr(USF)=0,0
Exp/Cntr=0.3,0.1

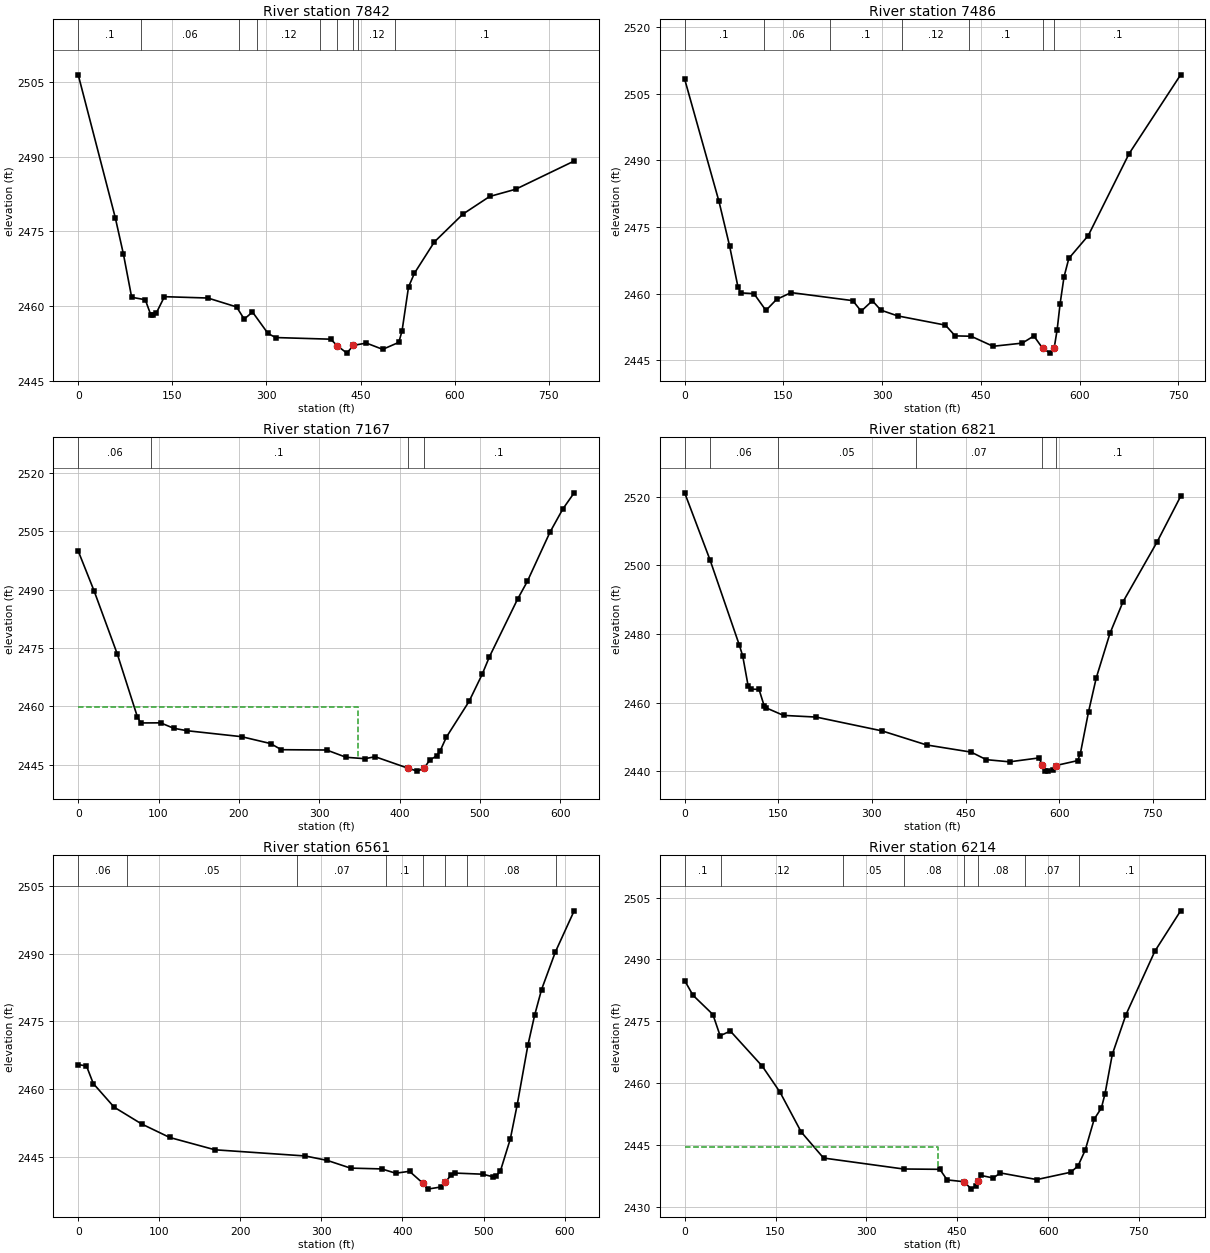
Type RM Length L Ch R = 1 ,7842    ,337.4,356.4,368
XS GIS Cut Line= 3
  2236686.517458391414.2127710692236515.85821845391487.078513795
2236047.98344937391870.582422882
#Sta/Elev= 30
       0 2506.47    59.1 2477.76    72.1 2470.43    85.2 2461.78   106.9 2461.29
   115.6 2458.28   119.6 2458.17   124.3 2458.57   137.4  2461.9   206.7 2461.63
   252.4 2459.84   264.6 2457.39   277.8 2458.82   302.5 2454.51   314.7 2453.69
   402.4 2453.36   412.7 2452.07   428.2 2450.56   438.6 2452.12   459.3 2452.58
   485.3 2451.32     511 2452.72   516.2 2455.05   526.5 2463.85   535.9 2466.61
   567.7  2472.9   613.2 2478.49   655.8 2482.03   697.2 2483.48   790.5 2489.15
#Mann= 9 ,-1,0
       0      .1       0     100     .06       0  255.56      .1       0
  285.56     .12       0  385.56      .1       0   412.7    .045       0
   438.6      .1       0  445.56     .12       0  505.56      .1       0
Bank Sta=412.7,438.6
XS Rating Curve= 0 ,0
Exp/Cntr(USF)=0,0
Exp/Cntr=0.3,0.1

Type RM Length L Ch R = 1 ,7486    ,324.8,318.3,309
XS GIS Cut Line= 4
2236672.14610169391382.374924718 2236341.0692338391502.676067227
2236118.78733944391397.0507855012235963.85622894391393.188510562
#Sta/Elev= 30
       0 2508.24    52.1 2480.74    68.1  2470.8    80.8  2461.6    85.1 2460.17
   105.2 2459.99   123.4 2456.22   139.5 2458.69   161.7 2460.23   255.3 2458.42
   268.1 2456.05   285.1  2458.4   297.9 2456.29   323.4 2454.99   396.1 2452.91
   410.8 2450.49   435.1 2450.41   468.4 2448.15   512.7 2448.86   530.4 2450.47
   543.7  2447.7   555.2 2446.61   561.2 2447.71   565.8 2451.92   570.2 2457.68
   576.2 2463.77   583.5 2467.92     613 2473.06     675 2491.48   753.3 2509.23
#Mann= 7 ,-1,0
       0      .1       0     120     .06       0     220      .1       0
     330     .12       0  432.26      .1       0   543.7    .045       0
   561.2      .1       0
Bank Sta=543.7,561.2
XS Rating Curve= 0 ,0
Exp/Cntr(USF)=0,0
Exp/Cntr=0.3,0.1

Type RM Length L Ch R = 1 ,7167    ,349.9,346,340.7
XS GIS Cut Line= 3
2236643.40405046391158.8671336352236494.96021682391120.455882727
2236034.25069727391174.742390909
#Sta/Elev= 30
       0 2499.92    19.9 2489.58    48.8 2473.32    73.6 2457.29    77.7 2455.69
   102.5 2455.72   118.9 2454.32   135.6 2453.69   203.3 2452.16   239.4 2450.39
   252.8 2448.81   309.2 2448.73   333.4 2446.86   356.6  2446.5   369.6    2447
   409.9 2444.09     422  2443.3   430.3 2444.02   437.5 2446.14   446.1 2447.22
   450.2 2448.41   458.2 2452.05   486.4 2461.23   502.7 2468.19   511.8 2472.73
   546.8 2487.54   558.9 2492.09   587.1 2504.75   603.1 2510.72   617.2 2514.88
#Mann= 4 ,-1,0
       0     .06       0      90      .1       0   409.9    .045       0
   430.3      .1       0
#XS Ineff= 2 , 0
          347.79 2459.76
Permanent Ineff=
       F       F
Bank Sta=409.9,430.3
XS Rating Curve= 0 ,0
Exp/Cntr=0.3,0.1

Type RM Length L Ch R = 1 ,6821    ,259,260.7,245.4
XS GIS Cut Line= 3
   2236697.39629       390594.252236083.94155183390861.666351819
2235963.96348548 390824.73319063
#Sta/Elev= 30
       0 2521.14    40.6 2501.61    87.4 2476.89      93 2473.62   101.7  2464.9
   106.1 2463.97   119.1  2463.9   127.4  2459.1   130.8 2458.49   158.4 2456.32
   210.8 2455.83   316.2 2451.81   387.7 2447.71     459 2445.63   483.3 2443.43
   520.6  2442.8   567.9 2443.94     573 2441.82   577.3 2440.14   581.7 2440.09
   590.4  2440.3   594.8 2441.72   629.7 2443.15     634 2445.16   647.1 2457.33
   659.5 2467.24   681.5 2480.23   702.4 2489.41   756.9  2506.8   794.7 2520.11
#Mann= 6 ,-1,0
       0      .1       0      40     .06       0     150     .05       0
     370     .07       0     573    .045       0   594.8      .1       0
Bank Sta=573,594.8
XS Rating Curve= 0 ,0
Exp/Cntr=0.3,0.1

Type RM Length L Ch R = 1 ,6561    ,340.6,346.6,341.9
XS GIS Cut Line= 2
2236517.55110621390433.4230855862235946.70941811390653.506627985
#Sta/Elev= 30
       0 2465.42    10.2  2465.1    18.6 2461.21    44.3 2455.97    78.2 2452.25
   112.9 2449.25   168.7 2446.52   280.1 2445.15   307.2 2444.17   335.9 2442.46
   374.4 2442.28   391.6 2441.33   408.7 2441.75   424.8 2439.18     431  2437.8
   447.3 2438.27   452.6 2439.29   460.2 2440.96     465 2441.36     499 2441.11
   511.6 2440.54   515.9  2440.8   520.7 2441.75   533.1 2448.96   541.6 2456.56
   554.7 2469.68   563.1  2476.4   571.6 2482.05   588.6 2490.37   611.8  2499.5
#Mann= 8 ,-1,0
       0     .06       0      60     .05       0     270     .07       0
     380      .1       0   424.8    .045       0   452.6      .1       0
     480     .08       0     590      .1       0
Bank Sta=424.8,452.6
XS Rating Curve= 0 ,0
Exp/Cntr(USF)=0,0
Exp/Cntr=0.3,0.1

Type RM Length L Ch R = 1 ,6214    ,425.9,420,402.6
XS GIS Cut Line= 4
2236521.53611727390255.9699772722236383.71578369390288.976263488
2235853.20204278 390282.584531672235744.74568091390381.063172726
#Sta/Elev= 30
       0 2484.87    13.7 2481.31    46.6 2476.63    58.5 2471.47    75.4 2472.61
   128.2 2464.06   157.3 2457.79   192.4  2448.1   229.3 2441.77   361.3 2439.11
   421.3 2439.03   433.3 2436.46   461.3 2436.02   473.3 2434.22     481 2435.07
   483.8 2436.28   489.3 2437.54   509.3 2436.93   521.3 2438.15   581.3 2436.54
   637.3 2438.32   649.3 2439.82   661.3 2443.69   676.1 2451.21     688 2453.93
     694  2457.4     706 2466.95   728.6  2476.6   776.3 2492.01   818.8 2501.81
#Mann= 8 ,-1,0
       0      .1       0      60     .12       0  261.72     .05       0
  361.72     .08       0   461.3    .045       0   483.8     .08       0
  561.72     .07       0  651.72      .1       0
#XS Ineff= 2 , 0
          418.64 2444.48
Permanent Ineff=
       F       F
Bank Sta=461.3,483.8
XS Rating Curve= 0 ,0
Exp/Cntr=0.3,0.1

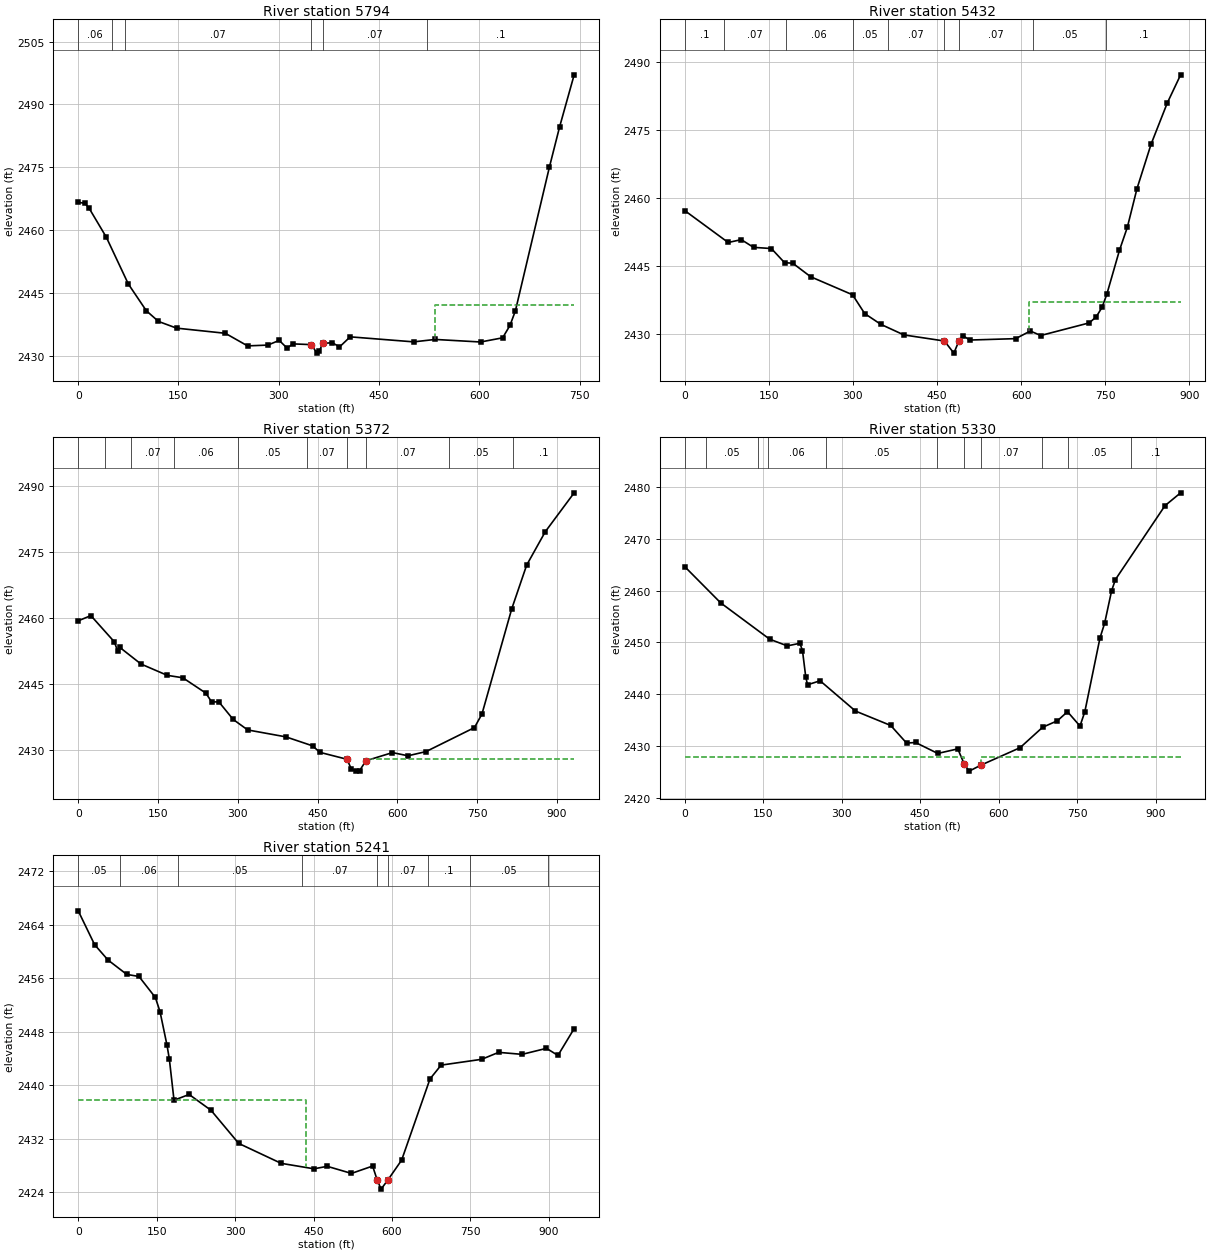
Type RM Length L Ch R = 1 ,5794    ,366.4,362.2,354.3
XS GIS Cut Line= 4
2236235.52803837389759.9021972662236139.91561363389795.996040909
 2235654.3411819390058.2510938932235597.63629892390125.505641913
#Sta/Elev= 30
       0 2466.59     9.8 2466.38      16 2465.27    42.1 2458.25      75 2447.08
   101.9  2440.7   120.1 2438.14   147.2 2436.54   220.1 2435.31   253.4  2432.3
   283.7 2432.49   300.7 2433.61   312.5 2431.77   321.3 2432.78   348.8  2432.6
   357.2 2430.57     361 2431.06   365.5 2432.91   380.4 2433.05   390.9 2432.04
   406.9 2434.46     502 2433.26     534 2433.84     602 2433.23     635 2434.23
     646 2437.19   654.1 2440.68     705 2475.03   720.1 2484.55     742 2497.06
#Mann= 6 ,-1,0
       0     .06       0      50     .05       0      70     .07       0
   348.8    .045       0   365.5     .07       0   522.2      .1       0
#XS Ineff= 2 , 0
                          533.89         2442.04
Permanent Ineff=
       F       F
Bank Sta=348.8,365.5
XS Rating Curve= 0 ,0
Exp/Cntr=0.3,0.1

Type RM Length L Ch R = 1 ,5432    ,57.1,60.2,65.7
XS GIS Cut Line= 3
2236128.63389326389389.1518998722235844.43258804389560.125593445
2235486.63333527389981.332308738
#Sta/Elev= 30
       0 2457.27    77.6 2450.23   100.9 2450.86   122.8 2449.16   154.6  2448.9
   178.1 2445.78   192.7 2445.67   224.6 2442.69   299.3 2438.72     321 2434.58
   349.6 2432.22   390.8 2429.88   463.1 2428.54     480 2425.87   488.7 2428.47
   495.7 2429.74   508.5 2428.75   590.2 2429.06   616.3 2430.74   634.8 2429.75
   721.4 2432.53   733.7 2433.85   744.1 2435.92   752.6 2438.79   775.3 2448.53
   789.3 2453.58   806.5 2462.09   831.6 2471.87   860.4 2480.92   884.3 2487.15
#Mann= 9 ,-1,0
       0      .1       0      70     .07       0     180     .06       0
     300     .05       0  361.67     .07       0   463.1    .045       0
   488.7     .07       0  621.67     .05       0  751.67      .1       0
#XS Ineff= 2 , 0
                          614.69         2437.22
Permanent Ineff=
       F       F
Bank Sta=463.1,488.7
XS Rating Curve= 0 ,0
Exp/Cntr(USF)=0,0
Exp/Cntr=0.5,0.3

Type RM Length L Ch R = 1 ,5372    ,43.3,41.9,41.4
XS GIS Cut Line= 4
2236111.42609203389329.1272869862235763.35602662389583.539945234
2235676.68797821389661.8207631572235457.22211368389977.739778344
#Sta/Elev= 30
       0 2459.32    23.8 2460.51    67.9 2454.56    73.9 2452.55    78.3 2453.29
     118 2449.53   167.5 2446.96   196.7 2446.41   239.9 2442.94   250.9 2440.94
   264.5 2440.94   291.4 2436.96   318.7 2434.58   390.5 2433.01   440.8 2430.97
   454.4  2429.5   505.4 2427.93   513.8 2425.66   523.1 2425.24   529.1 2425.34
     541 2427.59   590.9 2429.44   620.2 2428.72     654 2429.67   745.1 2435.11
   759.2 2438.18   815.2 2462.03   843.3 2471.96   878.3 2479.53   932.6 2488.35
#Mann= 10 ,-1,0
       0      .1       0      50     .05       0     100     .07       0
     180     .06       0     300     .05       0     430     .07       0
   505.4    .045       0     541     .07       0  697.92     .05       0
  817.92      .1       0
#XS Ineff= 2 , 0
          498.14    2428  546.08            2428
Permanent Ineff=
       F       F
Bank Sta=505.4,541
XS Rating Curve= 0 ,0
Exp/Cntr(USF)=0,0
Exp/Cntr=0.5,0.3

Type RM Length L Ch R = 1 ,5330    ,92.3,88.5,78.9
XS GIS Cut Line= 4
2236098.84524629389306.7613390082235756.36666788 389537.41017753
2235631.95608225389652.035660916 2235432.0604222389958.169573863
#Sta/Elev= 30
       0 2464.63    68.8 2457.63   162.4 2450.63   196.1 2449.34   220.2 2449.84
   225.1 2448.44   231.3  2443.4   234.7 2441.84   258.8 2442.61   326.4 2436.77
   393.8 2433.99     424  2430.6   441.2 2430.71   483.6  2428.6   521.9 2429.48
   534.6 2426.47   543.7 2425.19     566 2426.34   640.8  2429.7   683.9 2433.64
   712.4 2434.91   731.5 2436.65   755.4 2433.88   764.6 2436.62   793.6 2450.87
   802.4 2453.67   815.8 2459.96   823.1 2462.13   917.8 2476.37   947.7 2478.85
#Mann= 11 ,-1,0
       0      .1       0      40     .05       0     140     .07       0
     160     .06       0     270     .05       0   482.9     .07       0
   534.6    .045       0     566     .07       0  682.07      .1       0
  732.07     .05       0  852.07      .1       0
#XS Ineff= 2 , 0
          533.21    2428  567.18            2428
Permanent Ineff=
       F       F
Bank Sta=534.6,566
XS Rating Curve= 0 ,0
Exp/Cntr(USF)=0,0
Exp/Cntr=0.5,0.3

Type RM Length L Ch R = 1 ,5241    ,365.4,380.2,391.2
XS GIS Cut Line= 3
2236040.31635618 389292.908429982235656.47475273389483.130817531
 2235371.1411714389917.924846221
#Sta/Elev= 30
       0 2466.07    31.4    2461      57 2458.71    92.8 2456.56   116.2 2456.25
   147.5 2453.11   156.4    2451   169.8 2445.97   174.3 2443.88   183.2 2437.74
   212.1  2438.6     254 2436.23   306.9 2431.28     388  2428.3   450.8 2427.48
   476.3 2427.85   522.5 2426.79     563 2427.89   571.6 2425.84   579.2 2424.44
  592.112425.802   618.5 2428.78   672.7 2440.92     694 2442.99   771.6 2443.86
     804  2444.9   848.9  2444.6   895.5  2445.5   917.4 2444.44   948.4 2448.45
#Mann= 9 ,-1,0
       0     .05       0      80     .06       0     190     .05       0
  428.39     .07       0   571.6    .045       0  592.11     .07       0
  668.39      .1       0  748.39     .05       0  898.39      .1       0
#XS Ineff= 2 , 0
          435.22  2437.8
Permanent Ineff=
       F       F
Bank Sta=571.6,592.11
XS Rating Curve= 0 ,0
Exp/Cntr(USF)=0,0
Exp/Cntr=0.3,0.1