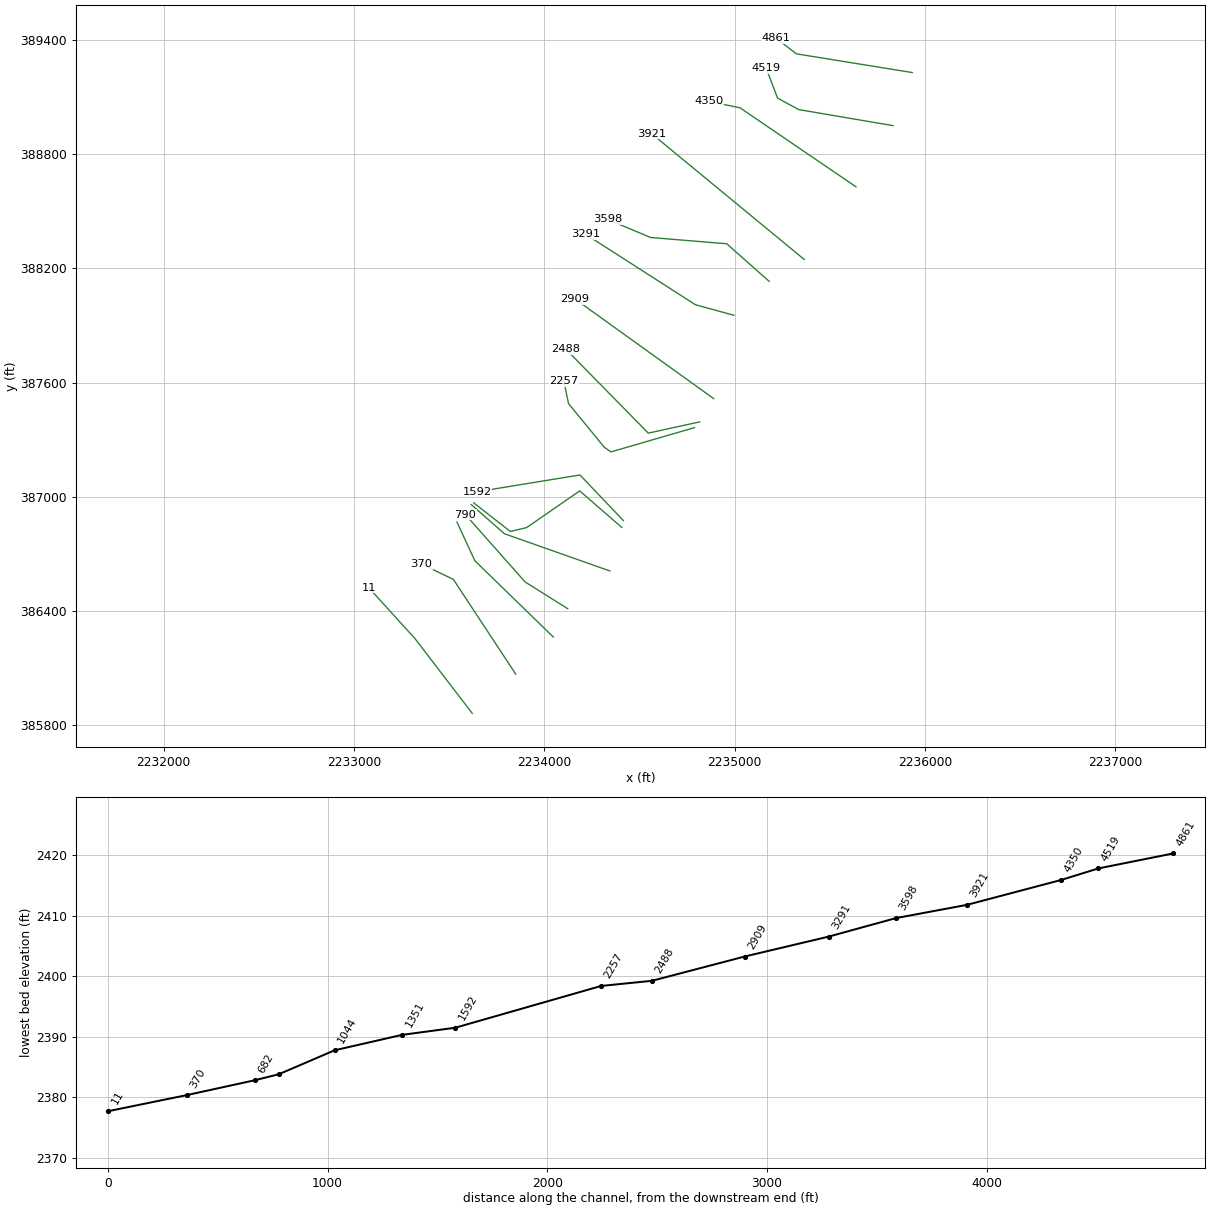
HEC-RAS study NFANTNYCK.prj: NFANTNYCK

--- NFANTNYCK.g01 (geometry) --- (continued)

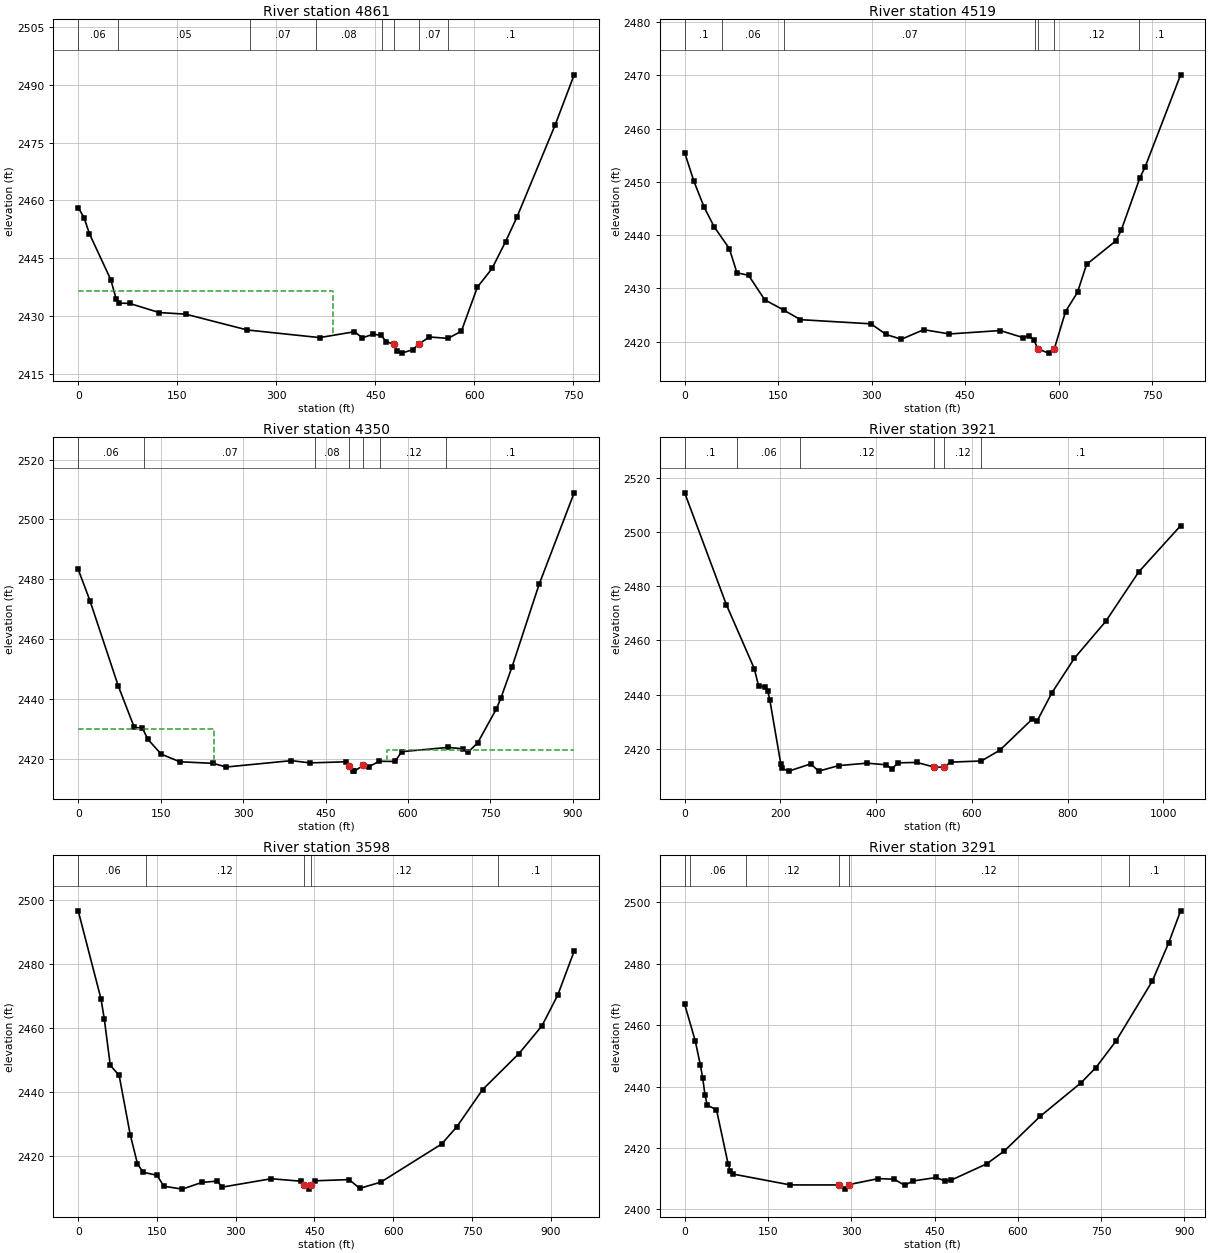
Type RM Length L Ch R = 1 ,4861    ,346.6,341.5,330.8
XS GIS Cut Line= 3
 2235932.9850139389228.2034862142235324.07951491389326.515699214
2235217.52470828389408.036448488
#Sta/Elev= 30
       0 2458.13     8.9 2455.49      17 2451.31    49.4 2439.37    57.5 2434.37
    61.6 2433.32    77.8 2433.24   122.4 2430.88   162.9 2430.45   255.9 2426.35
   365.5 2424.37   418.2 2425.89   430.3 2424.31   446.5 2425.25   458.6 2424.95
   466.8 2423.26   478.9 2422.65     483 2420.87     490 2420.34   507.2 2421.27
   515.4 2422.66   531.8 2424.53     560 2424.17   580.2 2426.03   604.5 2437.47
   626.7 2442.31   647.2 2449.31   664.3 2455.61   722.4 2479.64     751 2492.57
#Mann= 8 ,-1,0
       0     .06       0      60     .05       0     260     .07       0
     360     .08       0     460     .07       0   478.9    .045       0
   515.4     .07       0     560      .1       0
#XS Ineff= 2 , 0
          385.38 2436.39
Permanent Ineff=
       F       F
Bank Sta=478.9,515.4
XS Rating Curve= 0 ,0
Exp/Cntr=0.3,0.1

Type RM Length L Ch R = 1 ,4519    ,168.4,169.5,165.2
XS GIS Cut Line= 4
2235830.74191084388949.4613231292235335.55649593389033.792887057
 2235224.7288151389094.1937574912235165.29681341389250.250747976
#Sta/Elev= 30
       0 2455.49    14.8 2450.11      31 2445.32    47.2 2441.59    71.6 2437.49
    83.8 2432.95   102.5 2432.46   128.4 2427.87     160 2425.87   185.7 2424.14
   298.8 2423.36   323.2 2421.36   347.5 2420.46   383.4 2422.26   424.6 2421.46
   506.2  2422.1   542.6 2420.78   551.7 2421.12   560.4 2420.29   566.3 2418.68
   583.6 2417.86   592.8 2418.61   610.9 2425.67   630.1 2429.28   644.6 2434.51
   691.7 2438.94   700.2 2440.92   730.2 2450.78   738.7 2452.85   795.5  2470.1
#Mann= 7 ,-1,0
       0      .1       0      60     .06       0     160     .07       0
  562.32     .12       0   566.3    .045       0   592.8     .12       0
  728.53      .1       0
Bank Sta=566.3,592.8
XS Rating Curve= 0 ,0
Exp/Cntr(USF)=0,0
Exp/Cntr=0.3,0.1

Type RM Length L Ch R = 1 ,4350    ,430.2,429.3,427
XS GIS Cut Line= 3
2235636.78101282388628.0466609992235027.62456673389043.068746254
2234865.70738595389076.400682317
#Sta/Elev= 30
       0 2483.31    21.4 2472.84    73.2 2444.22     102 2430.56   116.9 2430.29
   126.6 2426.61   150.9 2421.64   184.7 2419.08   245.9 2418.54     269 2417.32
   387.9 2419.45   421.8  2418.7   487.8 2419.07   493.5 2417.77   499.2 2415.96
   502.2 2415.95   518.6 2417.83   528.3 2417.41   548.2 2419.24   576.7 2419.18
   588.5 2422.45   673.5 2423.88   700.8 2423.37   709.4  2422.3   726.8 2425.37
     761 2436.77   769.2  2440.4   789.6 2450.88   838.6  2478.3   902.4 2508.88
#Mann= 7 ,-1,0
       0     .06       0     120     .07       0     430     .08       0
   493.5    .045       0   518.6     .08       0     550     .12       0
     670      .1       0
#XS Ineff= 2 , 0
          247.51 2430.15  561.97         2422.87
Permanent Ineff=
       F       F
Bank Sta=493.5,518.6
XS Rating Curve= 0 ,0
Exp/Cntr=0.3,0.1

Type RM Length L Ch R = 1 ,3921    ,313.4,322.2,328.5
XS GIS Cut Line= 2
2235364.34691249388246.8120870252234564.67152775388905.986213693
#Sta/Elev= 30
       0 2514.45      87 2473.25   145.4 2449.65   154.6 2443.11   167.2 2442.97
   173.5 2441.49     178    2438   200.7 2414.61   203.6 2412.82   217.9 2411.85
   263.2 2414.49   280.1 2411.83   321.6 2413.86     381 2414.77   420.1 2414.17
   433.7 2412.65   445.1 2414.89   485.4 2415.03   521.8  2413.3   541.7 2413.28
   555.9 2415.15     620 2415.57   658.6 2419.56     726 2430.97   736.3 2430.28
   767.4 2440.73   814.5  2453.5   879.8 2467.05   948.9 2485.32  1036.3 2502.32
#Mann= 6 ,-1,0
       0      .1       0     110     .06       0     240     .12       0
   521.8    .045       0   541.7     .12       0     620      .1       0
Bank Sta=521.8,541.7
XS Rating Curve= 0 ,0
Exp/Cntr(USF)=0,0
Exp/Cntr=0.3,0.1

Type RM Length L Ch R = 1 ,3598    ,314.9,307.4,302.1
XS GIS Cut Line= 4
2235180.63552453388131.5130966672234957.78746565388328.916558337
2234557.93592947388361.7311220972234331.38301308388456.706994853
#Sta/Elev= 30
       0 2496.64    43.4  2469.1    49.7 2462.81      61 2448.39      78 2445.17
      99 2426.71   112.8 2417.62   123.2 2414.93   150.2 2413.99     163 2410.56
   198.3 2409.65   235.7 2411.76     265 2412.16     274 2410.27   367.6  2412.9
   423.7 2412.13   430.4 2410.87   439.8 2409.67   443.5 2410.92   451.8 2412.26
   516.1 2412.63   536.1 2409.89   576.3 2411.83   692.2 2423.75   721.2 2429.15
   770.2 2440.76   839.6 2452.04   883.2 2460.69   913.3 2470.27   944.6 2484.03
#Mann= 5 ,-1,0
       0     .06       0     130     .12       0   430.4    .045       0
   443.5     .12       0   798.9      .1       0
Bank Sta=430.4,443.5
XS Rating Curve= 0 ,0
Exp/Cntr(USF)=0,0
Exp/Cntr=0.3,0.1

Type RM Length L Ch R = 1 ,3291    ,380.6,382.1,384.2
XS GIS Cut Line= 3
2234995.47801439387953.1781493292234793.05045169388008.711374495
2234218.01286206388377.738612696
#Sta/Elev= 30
       0 2466.74      19 2454.91    28.3 2446.92    32.5 2442.73    36.6 2437.15
    40.8 2433.92    57.3 2432.43    78.1  2414.9    82.2 2412.41    86.4 2411.51
   190.1 2407.95   277.5 2407.94     289 2406.58   296.5 2408.08   348.8 2410.01
   377.3 2409.81   396.3 2407.82   410.7 2409.22   453.3 2410.37   468.5 2409.23
   480.1 2409.52   543.8 2414.81   575.6 2418.99   640.3  2430.3   714.4  2441.3
   740.7 2446.19   776.5 2454.74     842 2474.27   871.6 2486.74   893.2 2497.23
#Mann= 6 ,-1,0
       0      .1       0      10     .06       0     110     .12       0
   277.5    .045       0   296.5     .12       0  799.91      .1       0
Bank Sta=277.5,296.5
XS Rating Curve= 0 ,0
Exp/Cntr(USF)=0,0
Exp/Cntr=0.3,0.1

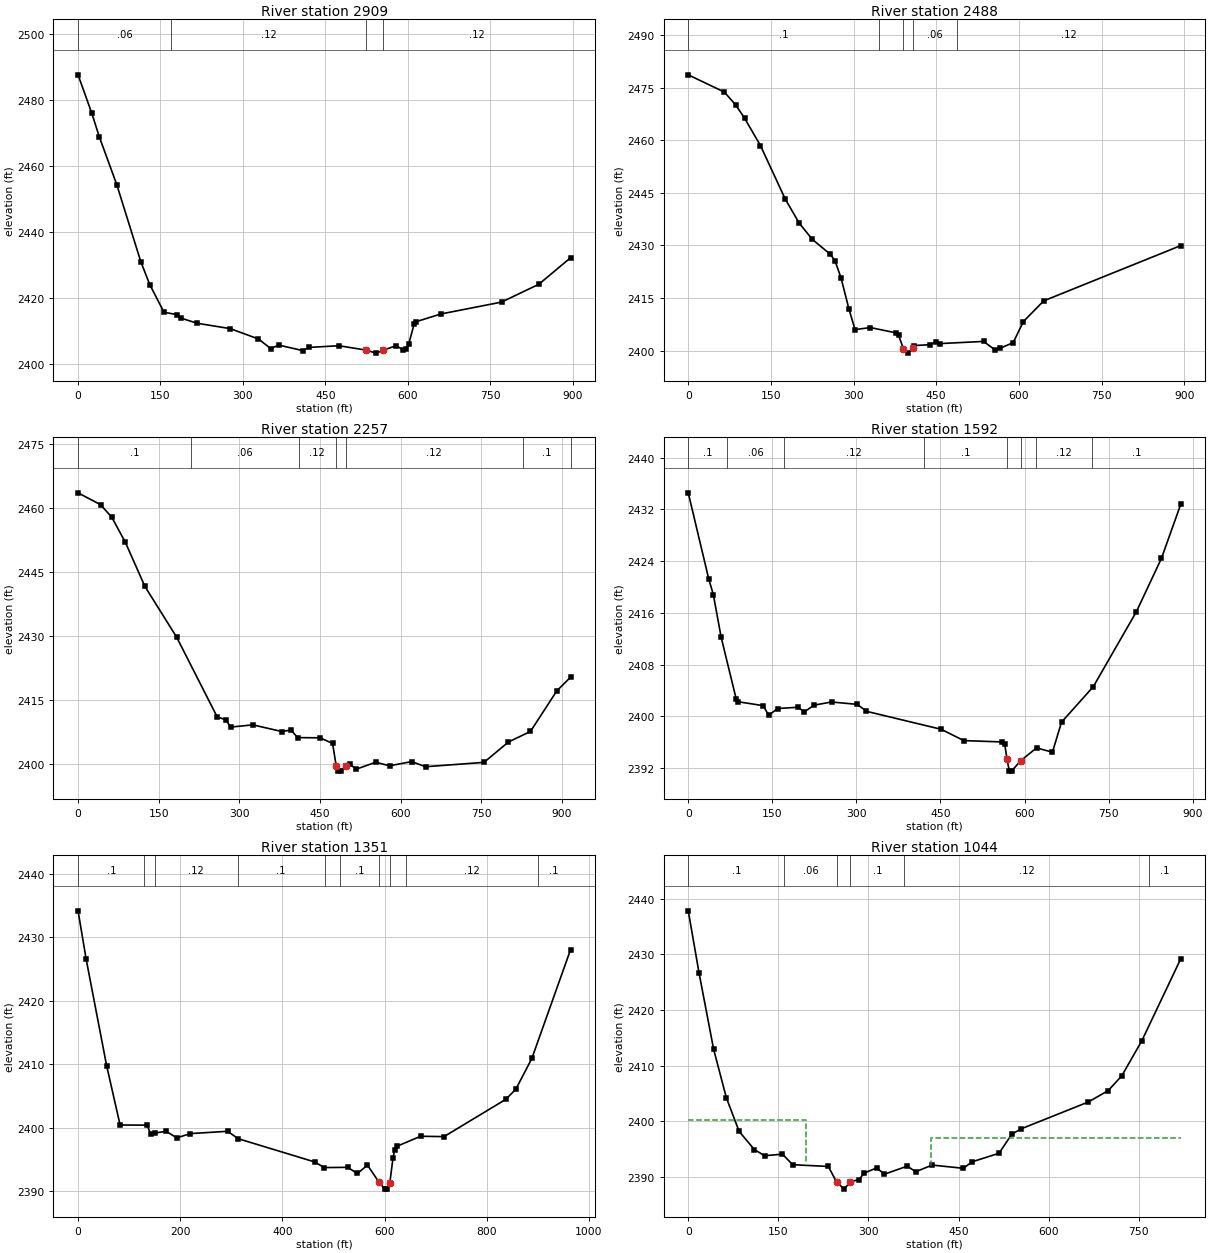
Type RM Length L Ch R = 1 ,2909    ,417.1,421.4,423.6
XS GIS Cut Line= 2
2234888.95152715387515.6937831142234160.82212644388038.510362747
#Sta/Elev= 30
       0 2487.56    24.6 2476.14    38.9 2468.69    70.4 2454.34   114.2 2430.99
   130.6 2424.01   156.4 2415.68   179.3 2414.96   188.1 2413.85   216.6 2412.34
   276.9 2410.71   328.4 2407.57   350.6 2404.68   365.4 2405.72   409.7 2404.03
   419.5 2405.01   474.6 2405.53   523.3 2404.23   542.6 2403.29   555.7 2404.17
   578.6 2405.54   591.9 2404.31   596.8 2404.66   601.7    2406   611.6 2412.06
     615  2412.8   660.8 2415.16   770.7 2418.74   838.6 2424.14   896.4 2432.18
#Mann= 4 ,-1,0
       0     .06       0     170     .12       0   523.3    .045       0
   555.7     .12       0
Bank Sta=523.3,555.7
XS Rating Curve= 0 ,0
Exp/Cntr(USF)=0,0
Exp/Cntr=0.3,0.1

Type RM Length L Ch R = 1 ,2488    ,228.2,231.1,230.4
XS GIS Cut Line= 3
2234816.14898673387393.3052565342234545.73550729387334.090626436
2234113.37861767387774.185151211
#Sta/Elev= 30
       0  2478.7    65.5 2473.78      86 2470.14   102.3 2466.29     131 2458.53
     176 2443.25   201.6 2436.32   225.2 2431.74   257.9 2427.47   266.1 2425.71
   277.3 2420.74   291.4 2411.99   302.7 2405.99   330.4 2406.58   376.5 2405.08
   381.8 2404.32   390.4 2400.57   398.9 2399.28   407.4 2400.61   410.3 2401.45
   438.2 2401.68   449.8 2402.53     456    2402   535.9 2402.62   555.9  2400.3
   565.8 2400.65   589.6 2402.28   608.2 2408.29     645 2414.19   893.8 2429.97
#Mann= 5 ,-1,0
       0      .1       0  346.82     .06       0   390.4    .045       0
   407.4     .06       0  486.82     .12       0
#XS Ineff= 2 , 0
          194.35 2411.04
Permanent Ineff=
       F       F
Bank Sta=390.4,407.4
XS Rating Curve= 0 ,0
Exp/Cntr(USF)=0,0
Exp/Cntr=0.3,0.1

Type RM Length L Ch R = 1 ,2257    ,645.1,664.4,674.6
XS GIS Cut Line= 5
2234788.35707158387363.0824360442234349.39545099387235.361063835
2234314.81895313387259.6136151232234126.57656684 387489.46127007
2234102.21536117387606.238820335
#Sta/Elev= 30
       0 2463.53    41.8 2460.76    62.7 2457.82    87.7 2452.02   124.3 2441.64
   183.5 2429.73   258.5 2411.16   275.1  2410.4   283.5 2408.73   325.1 2409.25
   379.1 2407.69   395.9 2408.04   408.4 2406.27   450.1 2406.22   473.3 2404.91
479.93622399.676   483.1  2398.5     488 2398.43497.69622399.717   505.2 2400.11
   516.9 2398.87   553.6 2400.51   579.1 2399.67   620.3 2400.66   646.2 2399.46
   754.8 2400.48   800.3 2405.25   841.2 2407.71   890.2  2417.2   915.8 2420.41
#Mann= 7 ,-1,0
       0      .1       0     210     .06       0     410     .12       0
479.9362    .045       0497.6962     .12       0  826.49      .1       0
  915.79     .12       0
Bank Sta=479.9362,497.6962
XS Rating Curve= 0 ,0
Exp/Cntr(USF)=0,0
Exp/Cntr=0.3,0.1

Type RM Length L Ch R = 1 ,1592    ,229.4,240.8,242.9
XS GIS Cut Line= 3
2234415.03252131386874.637831263 2234186.8476954387114.327774442
2233646.10718359387026.121875352
#Sta/Elev= 30
       0 2434.55    36.6 2421.22    44.8  2418.8    58.7 2412.22    85.4 2402.73
    88.7 2402.25     134 2401.64   143.4 2400.14   159.4  2401.2   195.6 2401.39
   207.2 2400.68   224.4 2401.72   255.6 2402.21   301.7 2401.84   317.9 2400.77
   451.2 2397.99   491.7 2396.24   560.6 2396.03   564.7  2395.7   568.7 2393.38
   572.8 2391.56   576.8 2391.52     593 2393.12   621.4 2395.11   649.8 2394.45
     666 2399.09   722.7 2404.58   799.7 2416.19   844.3 2424.42   878.8  2432.8
#Mann= 8 ,-1,0
       0      .1       0      70     .06       0     170     .12       0
  420.94      .1       0   568.7    .045       0     593      .1       0
  620.94     .12       0  720.94      .1       0
Bank Sta=568.7,593
XS Rating Curve= 0 ,0
Exp/Cntr(USF)=0,0
Exp/Cntr=0.3,0.1

Type RM Length L Ch R = 1 ,1351    ,324.3,307.5,295.3
XS GIS Cut Line= 5
2234406.35120262386838.8161195962234185.33714167387030.687665522
2233906.86985614386837.9929424872233821.13477702386817.338351317
2233628.47900005386967.988485231
#Sta/Elev= 30
       0 2434.14    15.8 2426.57    55.9 2409.79    82.3 2400.44   135.3 2400.42
   142.2 2398.98     150 2399.17   172.4 2399.45   193.2 2398.42   220.1 2399.09
   292.7 2399.45   313.6 2398.28   464.3  2394.6   481.5 2393.74   527.5 2393.78
     547 2392.81   566.5 2394.13   589.3 2391.42   600.5 2390.35   605.4 2390.43
   610.3 2391.36   616.6 2395.32     620 2396.58   624.9 2397.12   670.7 2398.67
   716.4 2398.61   836.9 2404.46   856.9 2406.06   888.3 2410.92   964.1 2428.04
#Mann= 10 ,-1,0
       0      .1       0     130     .06       0     150     .12       0
  312.68      .1       0  482.68     .12       0  512.68      .1       0
   589.3    .045       0   610.3      .1       0  641.32     .12       0
  899.51      .1       0
Bank Sta=589.3,610.3
XS Rating Curve= 0 ,0
Exp/Cntr(USF)=0,0
Exp/Cntr=0.3,0.1

Type RM Length L Ch R = 1 ,1044    ,264.5,254.1,249.1
XS GIS Cut Line= 3
2234344.08429813386610.020133992 2233789.9211495386805.607127627
2233615.42687086386959.008691262
#Sta/Elev= 30
       0 2437.79    18.1 2426.56    42.3  2412.9    63.5  2404.2    84.7 2398.17
   110.2  2394.9   127.2  2393.8   156.9 2394.08   173.8 2392.19   233.2 2391.87
     247 2389.07   259.5  2387.8  270.122389.153   284.1 2389.49   292.6 2390.66
   313.8 2391.62   326.5 2390.48   364.7 2391.93   378.6 2390.92   406.1 2392.12
     458 2391.54   472.7 2392.71   517.4 2394.24   538.5 2397.65   554.2 2398.63
   665.8 2403.44   699.1 2405.49   721.8 2408.16   755.1 2414.44     820 2429.19
#Mann= 6 ,-1,0
       0      .1       0     160     .06       0     247    .045       0
  270.12      .1       0     360     .12       0  767.67      .1       0
#XS Ineff= 2 , 0
          196.01  2400.2  404.28         2396.91
Permanent Ineff=
       F       F
Bank Sta=247,270.12
XS Rating Curve= 0 ,0
Exp/Cntr(USF)=0,0
Exp/Cntr=0.3,0.1

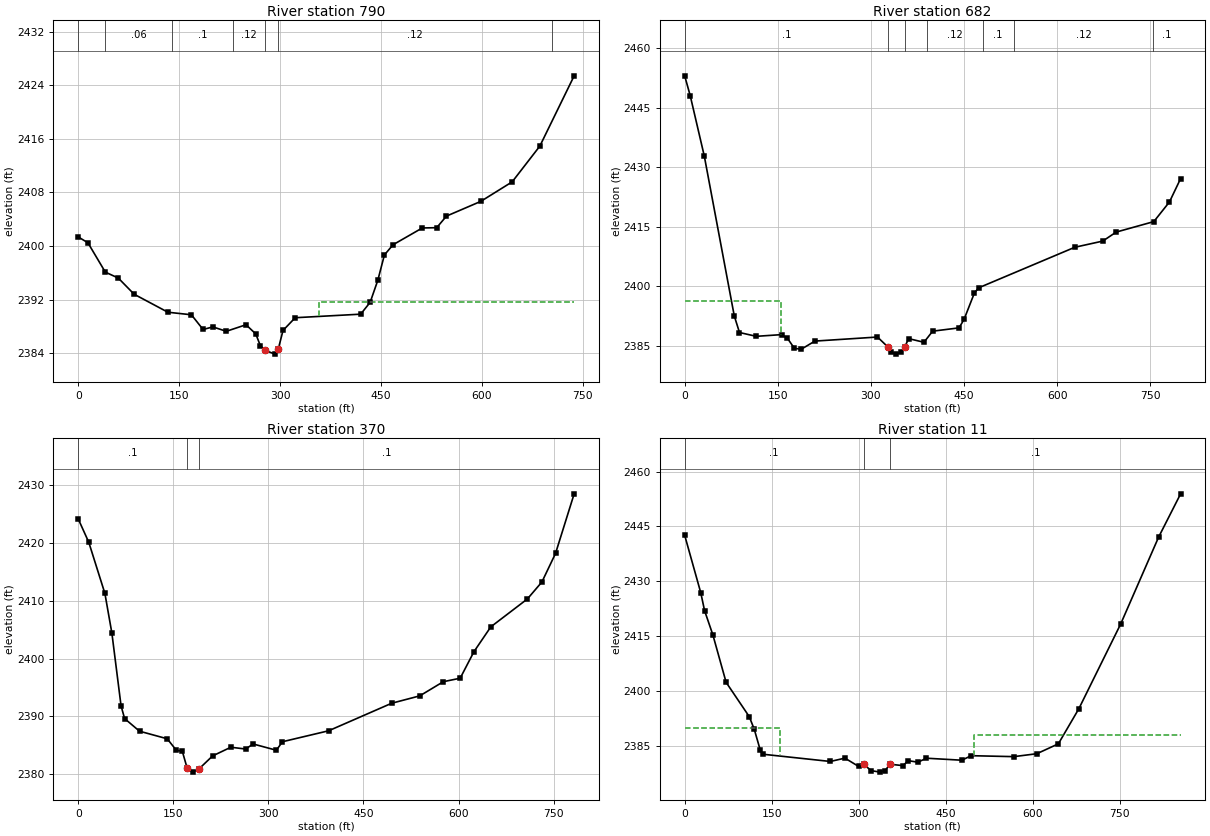
Type RM Length L Ch R = 1 ,790     ,105.8,107.4,108.7
XS GIS Cut Line= 3
2234122.55097288386411.7265153072233898.93646514386552.112304915
 2233585.0739498386906.085045856
#Sta/Elev= 30
       0 2401.35    14.4 2400.48    40.3 2396.09    59.5 2395.21    83.1 2392.79
   133.3  2390.1   168.2 2389.72   185.6 2387.52   200.1 2387.91   220.1 2387.25
   249.4 2388.23   263.9 2386.86   270.8 2385.08   278.1  2384.4   292.3 2383.84
   297.5 2384.66   304.4 2387.38   322.5 2389.28   419.8 2389.81   433.9 2391.58
   445.3 2394.88   455.1 2398.66   467.9 2400.18   511.4 2402.69   532.8 2402.73
   547.3 2404.46   598.3 2406.66     645 2409.58   686.1 2414.92   737.1 2425.42
#Mann= 7 ,-1,0
       0      .1       0      40     .06       0     140      .1       0
     230     .12       0   278.1    .045       0   297.5     .12       0
  704.03      .1       0
#XS Ineff= 2 , 0
                          357.57         2391.65
Permanent Ineff=
       F       F
Bank Sta=278.1,297.5
XS Rating Curve= 0 ,0
Exp/Cntr(USF)=0,0
Exp/Cntr=0.3,0.1

Type RM Length L Ch R = 1 ,682     ,313.2,312.7,312.7
XS GIS Cut Line= 3
2234046.86876859386262.9490962682233634.60206632386663.710681265
2233540.64360859386866.967753081
#Sta/Elev= 30
       0 2453.05     8.9 2448.06    31.6 2432.81    79.9 2392.49    88.3 2388.31
   115.3 2387.35   156.2 2387.78   165.5 2386.86   176.7 2384.32   187.8  2384.1
   209.8 2386.15   310.6 2387.17   327.3 2384.67   332.9 2383.31   340.1 2382.86
   348.6 2383.34   354.2 2384.59   360.8 2386.77   385.4 2385.85   399.5 2388.65
   441.9 2389.48     450  2391.6   466.8 2398.32   473.8  2399.6   628.4 2409.81
   673.5 2411.37   695.1 2413.64   755.7 2416.28   780.9 2421.24   798.9 2427.13
#Mann= 7 ,-1,0
       0      .1       0   327.3    .045       0   354.2      .1       0
     390     .12       0     480      .1       0     530     .12       0
  754.96      .1       0
#XS Ineff= 2 , 0
          155.28  2396.2
Permanent Ineff=
       F       F
Bank Sta=327.3,354.2
XS Rating Curve= 0 ,0
Exp/Cntr(USF)=0,0
Exp/Cntr=0.3,0.1

Type RM Length L Ch R = 1 ,370     ,358.1,358.1,358.1
XS GIS Cut Line= 3
2233849.35239371386068.054594803 2233521.7612361386565.822977149
2233353.71122668386646.657158897
#Sta/Elev= 30
       0 2424.12    16.7 2420.07    42.1 2411.24    53.1  2404.4    67.6 2391.82
    73.2 2389.63    96.7 2387.45   140.4 2386.14   154.9 2384.14   164.2 2383.99
     172 2381.02   180.7 2380.38  191.012380.982     212 2383.18   240.8 2384.68
   264.1 2384.37     276 2385.24   312.6 2384.16   322.2 2385.63     395 2387.52
   494.6 2392.28   538.8 2393.55     576    2396   602.6  2396.6   624.3 2401.18
   650.9 2405.47   708.6 2410.29   731.5 2413.22     753 2418.15   782.4 2428.45
#Mann= 3 ,-1,0
       0      .1       0     172    .045       0  191.01      .1       0
Bank Sta=172,191.01
XS Rating Curve= 0 ,0
Exp/Cntr(USF)=0,0
Exp/Cntr=0.3,0.1

Type RM Length L Ch R = 1 ,11      ,372.3,374.8,377.3
XS GIS Cut Line= 3
 2233621.0238103385861.9389685542233321.02375413386253.605508059
2233078.31557813386521.313962147
#Sta/Elev= 30
       0 2442.57    27.7 2426.85    34.3 2421.93    48.6 2415.29    71.4 2402.31
   111.3 2392.91     120 2389.41     130 2383.88   134.2 2382.63     251 2380.64
   276.2 2381.55   299.6  2379.3   308.52379.841   321.5 2378.13   336.7 2377.72
   345.3 2378.13   353.9 2379.88   376.3  2379.5   385.2 2380.86   402.1 2380.44
   416.6 2381.53   477.7 2380.98   493.7 2382.22   567.3 2381.96   606.9 2382.76
     644 2385.47   679.2 2395.05   751.4 2418.28   816.7 2442.04   854.7 2453.92
#Mann= 3 ,-1,0
       0      .1       0   308.5    .045       0   353.9      .1       0
#XS Ineff= 2 , 0
          164.12  2389.9  498.02         2388.02
Permanent Ineff=
       F       F
Bank Sta=308.5,353.9
XS Rating Curve= 0 ,0
Exp/Cntr=0.3,0.1
LCMann Table=0

Chan Stop Cuts=-1
Use User Specified Reach Order=0
Composite Channel Slope=5